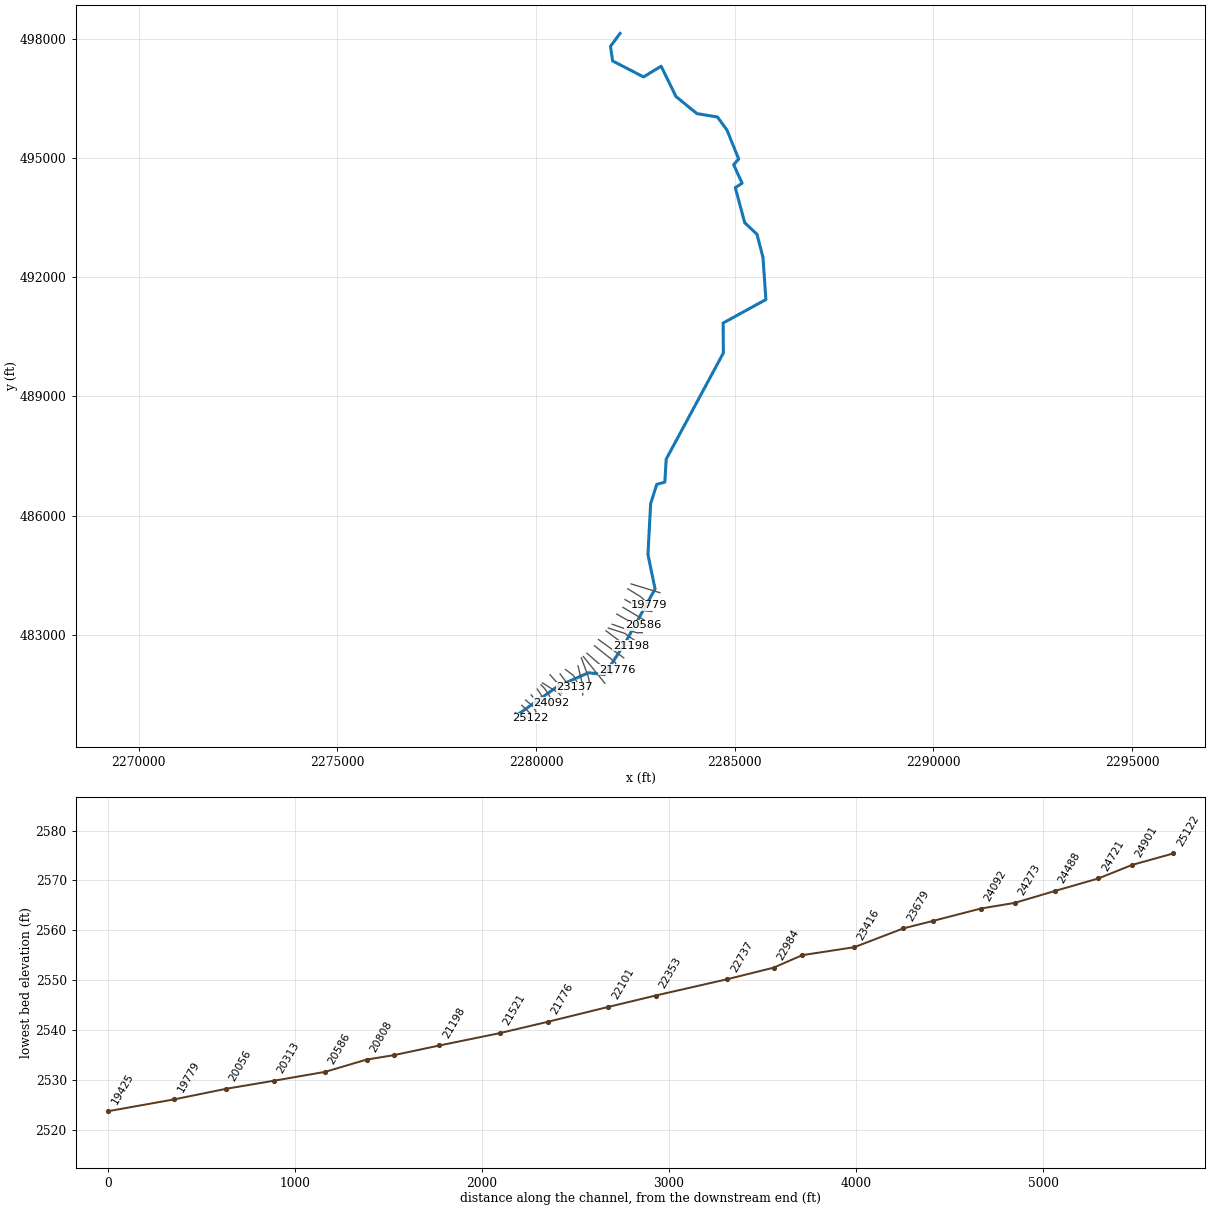
--- THOMASCK.prj (project) ---

Proj Title=THOMASCK
Current Plan=p01
Default Exp/Contr=0,0
English Units
Geom File=g01
Flow File=f01
Plan File=p01
Background Map Layer=Inundation Boundary (01pct Value_0)
BEGIN DESCRIPTION:
----------MODEL BY WOOD PLC 2021----------
Stream Name: Thomas Creek
Flood Zone: Approximate
Pocahontas County, WV
HEC-RAS Version: RAS 6.0
Vertical Datum: NAVD88
Projection: NAD 1983 StatePlane West Virginia S FIPS 4702 (US Feet)
Terrain: 1-meter LIDAR (FEMA Region III 3DEP collected 2016-2018)
Land Use: 2019 NLCD
Hydrologic Method:
WV SIR2010-5033 regression equations
Model Notes:
END DESCRIPTION:
DSS Export Rating Curves= 0
DSS Export Rating Curve Sorted= 0
DSS Export Volume Flow Curves= 0
DXF OffsetX= 0
DXF OffsetY= 0
DXF ScaleX= 0
DXF ScaleY= 0

--- THOMASCK.p01 (plan) ---

Plan Title=Floodplain
Program Version=6.00
Short Identifier=Floodplain
Geom File=g01
Flow File=f01
Subcritical Flow
K Sum by GR= 0
Std Step Tol= 0.01
Critical Tol= 0.01
Num of Std Step Trials= 20
Max Error Tol= 0.3
Flow Tol Ratio= 0.001
Split Flow NTrial= 30
Split Flow Tol= 0.02
Split Flow Ratio= 0.02
Log Output Level= 0
Friction Slope Method= 1
Unsteady Friction Slope Method= 2
Unsteady Bridges Friction Slope Method= 1
Parabolic Critical Depth
Global Vel Dist= 0 , 0 , 0
Global Log Level= 0
CheckData=True
Encroach Param=-1 ,0,0, 0
Mapping Interval=1HOUR
Computation Time Step Use Courant=        0
Computation Time Step Use Time Series=    0
Computation Time Step Count To Double=0
Computation Time Step Max Doubling=0
Computation Time Step Max Halving=0
Computation Time Step Residence Courant=0
Run HTab= 0
Run UNet= 0
Run Sediment= 0
Run PostProcess= 0
Run WQNet= 0
Run RASMapper=-1
UNET Theta= 0
UNET Theta Warmup= 0
UNET ZTol= 0
UNET ZSATol= 0
UNET MxIter= 0
UNET Max Iter WO Improvement= 0
UNET MaxInSteps= 0
UNET DtIC= 0
UNET DtMin= 0
UNET MaxCRTS= 0
UNET WFStab= 0
UNET SFStab= 0
UNET WFX= 1
UNET SFX= 1
UNET Gravity=32.174
UNET 1D Methodology=Finite Difference
UNET DSS MLevel= 1
UNET Pardiso=0
UNET DZMax Abort= 0
UNET Use Existing IB Tables= 0
UNET Froude Reduction=False
UNET Froude Limit= 0
UNET Froude Power= 0
UNET D1 Cores= 0
UNET WindReference=Eulerian
UNET WindDragFormulation=Hsu (1988)
UNET D2 Coriolis=0
UNET D2 Cores= 0
UNET D2 Theta= 1
UNET D2 Theta Warmup= 1
UNET D2 Z Tol= 0.01
UNET D2 Volume Tol= 0.01
UNET D2 Max Iterations= 20
UNET D2 Equation= 0
UNET D2 RampUpFraction=0.1
UNET D2 TimeSlices= 1
UNET D2 Turbulence Formulation=Non-Conservative (original)
UNET D2 Eddy Viscosity=0.3
UNET D2 Transverse Eddy Viscosity=0.1
UNET D2 Smagorinsky Mixing=0
UNET D2 BCVolumeCheck=0
UNET D2 Cores=0
UNET D2 SolverType=PARDISO (Direct)
UNET D2 Minimum Iterations= 2147483647
UNET D2 Maximum Iterations= 2147483647
UNET D2 Restart Number= 10
UNET D2 Relaxation Coeff=1.3
UNET D2 SOR Precondition Iterations= 10
UNET D2 ILUT Maximum Fill= 8
UNET D2 ILUT Tolerance=1E-08
UNET D1D2 MaxIter= 0
UNET D1D2 ZTol=0.01
UNET D1D2 QTol=0.1
UNET D1D2 MinQTol=1
Write IC File= 0
Write IC File at Fixed DateTime=0
Write IC File at Sim End=0
Echo Input=False
Echo Parameters=False
Echo Output=False
Write Detailed= 0
HDF Write Warmup=0
HDF Write Time Slices=0
HDF Flush=0
HDF Compression= 1
HDF Chunk Size= 1
HDF Spatial Parts= 1
HDF Use Max Rows=0
HDF Fixed Rows= 1
Calibration Method= 0
Calibration Iterations= 20
Calibration Max Change=0.05
Calibration Tolerance=0.2
Calibration Maximum=1.5
Calibration Minimum=0.5
Calibration Optimization Method= 1
WQ AD Non Conservative
WQ ULTIMATE=-1
WQ Max Comp Step=1HOUR
WQ Output Interval=15MIN
WQ Output Selected Increments= 0
WQ Output face flow=0
WQ Output face velocity=0
WQ Output face area=0
WQ Output face dispersion=0
WQ Output cell volume=0
WQ Output cell surface area=0
WQ Output cell continuity=0
WQ Output cumulative cell continuity=0
WQ Output face conc=0
WQ Output face dconc_dx=0
WQ Output face courant=0
WQ Output face peclet=0
WQ Output face adv mass=0
WQ Output face disp mass=0
WQ Output cell mass=0
WQ Output cell source sink temp=0
WQ Output nsm pathways=0
WQ Output nsm derived pathways=0
WQ Create Restart=0
WQ Fixed Restart=0
WQ System Summary=0
WQ Write To DSS=0
Sorting and Armoring Iterations= 10
XS Update Threshold= 0.02
Bed Roughness Predictor= 0
Hydraulics Update Threshold= 0.02
Energy Slope Method= 1
Volume Change Method= 1
Sediment Retention Method= 0
Sediment TS Multiplier= 1
Warm Up Method= 0
XS Weighting Method= 0
Number of US Weighted Cross Sections= 1
Number of DS Weighted Cross Sections= 1
Upstream XS Weight=0
Main XS Weight=1
Downstream XS Weight=0
Number of DS XS's Weighted with US Boundary= 1
Upstream Boundary Weight= 1
Weight of XSs Associated with US Boundary= 0
Number of US XS's Weighted with DS Boundary= 1
Downstream Boundary Weight= 0.5
Weight of XSs Associated with DS Boundary= 0.5
Percentile Method= 0
Sediment Output Level= 3
Mass or Volume Output= 0
Output Increment Type= 1
Profile and TS Output Increment= 1
Transport Output Increment 1
XS Output Flag= 0
XS Output Increment= 10
Read HDF5 Sediment Hotstart= 0
Sediment Hotstart Type= 0
Write Gradation File= 0
Read Gradation Hotstart= 0
Write HDF5 File= 1
Write Binary Output= 1
Write DSS Sediment File= 0
DSS Sediment Output Type= 1
SV Curve= 0
Specific Gage Flag= 0
Subcell Erosion Methods= 0
Subcell Deposition Methods= 0
Advection Scheme= 1
Matrix Solver= 0
Implicit Weighting Factor= 1
Maximum Outer Loop Convergence Iterations= 5
Convergence Maximum Absolute= 0.001
Convergence RMSE= 0.0001
Grain Fractions Max Abs Error= 0.001
Max Subgrid Regions= 1
Max Subgrid Length Scale= 3.402823E+38
Initial Layer Thickness= 3.402823E+38
Min Layer Thickness= 3.402823E+38
Max Layer Thickness= 3.402823E+38
Number of Layers= 5

--- THOMASCK.f01 (steady flow) ---

Flow Title=Flow
Program Version=6.00
Number of Profiles= 6
Profile Names=01pct,10pct,04pct,02pct,0_2pct,01plus
River Rch & RM=THOMASCK,Main            ,25122
     682     363     481     578     949    1010
River Rch & RM=THOMASCK,Main            ,22737
     794     425     562     674    1100    1170
River Rch & RM=THOMASCK,Main            ,21198
     891     479     632     757    1230    1320
River Rch & RM=THOMASCK,Main            ,16163
    1090     588     772     924    1500    1600
River Rch & RM=THOMASCK,Main            ,15231
    1220     662     868    1040    1670    1800
River Rch & RM=THOMASCK,Main            ,12861
    1450     793    1040    1240    1990    2140
River Rch & RM=THOMASCK,Main            ,10277
    1710     941    1230    1460    2340    2520
Boundary for River Rch & Prof#=THOMASCK,Main            , 1
Up Type= 0
Dn Type= 3
Dn Slope=0.00502
Boundary for River Rch & Prof#=THOMASCK,Main            , 2
Up Type= 0
Dn Type= 3
Dn Slope=0.00502
Boundary for River Rch & Prof#=THOMASCK,Main            , 3
Up Type= 0
Dn Type= 3
Dn Slope=0.00502
Boundary for River Rch & Prof#=THOMASCK,Main            , 4
Up Type= 0
Dn Type= 3
Dn Slope=0.00502
Boundary for River Rch & Prof#=THOMASCK,Main            , 5
Up Type= 0
Dn Type= 3
Dn Slope=0.00502
Boundary for River Rch & Prof#=THOMASCK,Main            , 6
Up Type= 0
Dn Type= 3
Dn Slope=0.00502
DSS Import GetInterval= 0
DSS Import GetPeak= 0
DSS Import FillOption= 0

--- THOMASCK.g01 (geometry) ---

Geom Title=Geometry
Program Version=6.00

River Reach=THOMASCK        ,Main
Reach XY= 30
2279567.41331277481015.630324474     2280546.413      481706.945
     2281318.473      482048.0772281721.41564468482001.099521278
2282223.10064397482768.735008511     2282993.881      484155.848
     2282815.095      485023.264     2282882.669      486304.969
     2283037.216      486789.275     2283239.436      486844.261
     2283274.803      487424.631     2284712.623      490094.224
     2284706.948      490848.766     2285783.144      491439.444
     2285709.641       492499.31      2285558.89      493080.326
     2285249.762      493373.889     2285013.095      494255.436
2285183.81980973      494366.029     2284971.918         494833.
     2285098.408      494974.822     2284802.203      495706.663
     2284564.338      496032.258     2284049.408      496117.552
     2283520.541      496546.907     2283147.197      497311.018
2282704.41966947497041.932903252     2281925.749      497443.658
     2281871.406      497810.581     2282113.024      498136.469

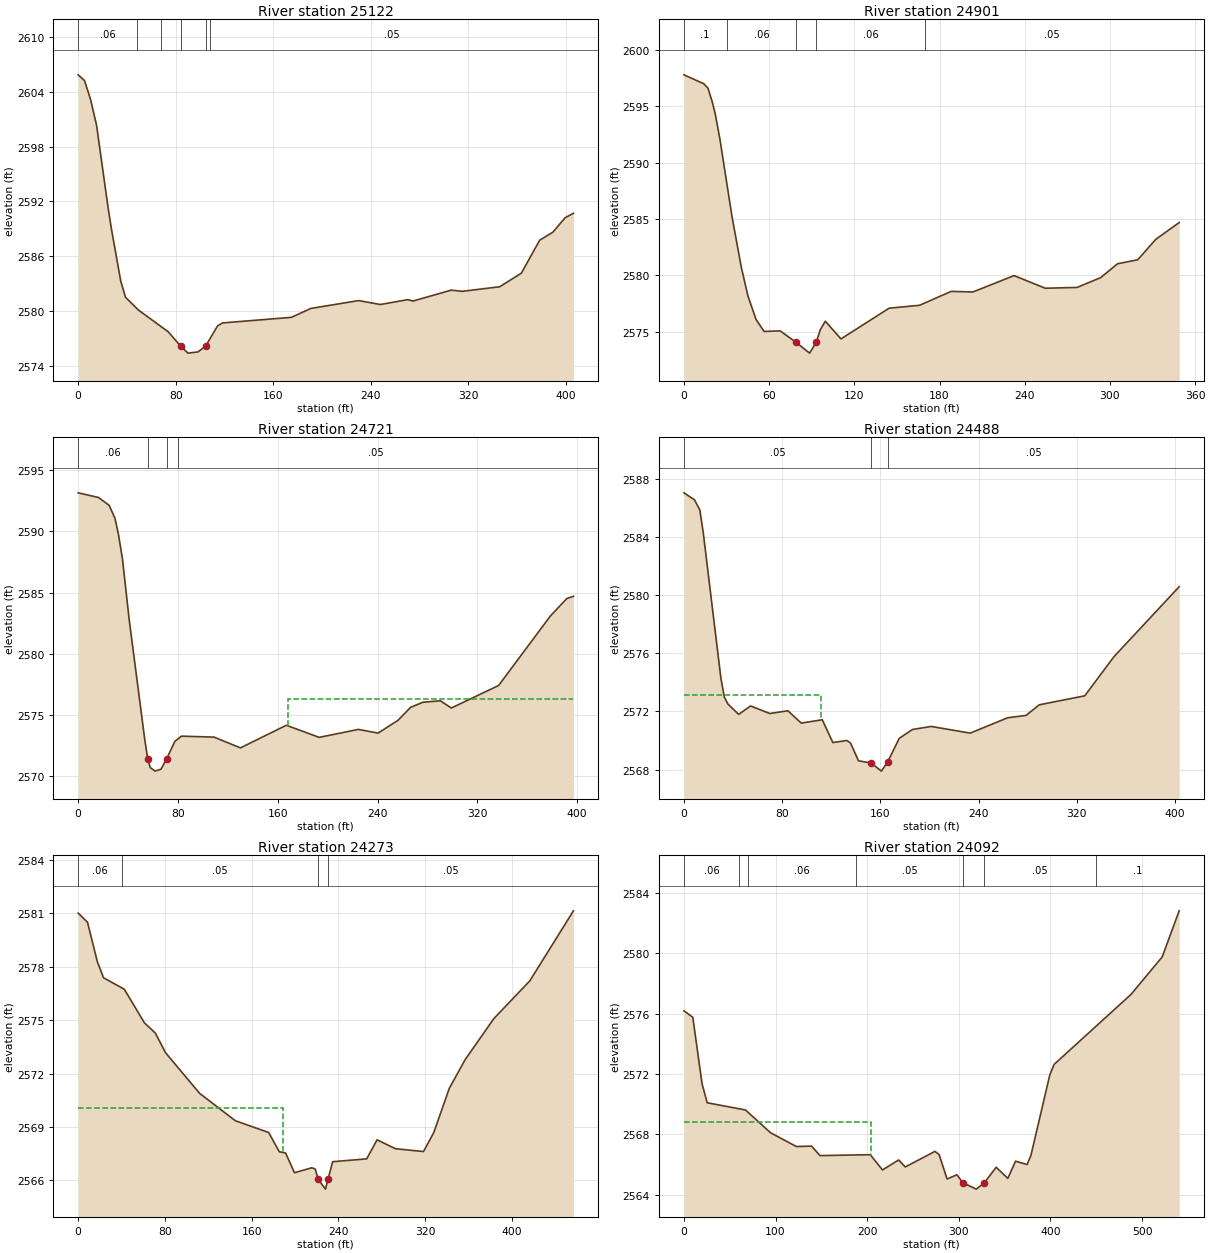
Type RM Length L Ch R = 1 ,25122   ,221.2,221.2,221.2
XS GIS Cut Line= 4
2279480.00781669481043.246111264 2279518.7358009481015.009152194
2279591.61019451481028.8633905982279845.83844931480901.589498385
#Sta/Elev= 30
       0 2605.83     5.2  2605.2    10.1 2603.17    15.1 2600.32    24.5 2591.35
    27.4 2588.91    34.9 2583.32    38.8 2581.54    49.4 2580.14    73.8 2577.77
   84.07  2576.2    90.1 2575.43    98.3 2575.56  104.64 2576.21   114.5 2578.43
   118.6 2578.73     175 2579.34   190.9 2580.31   230.1 2581.17     248 2580.74
   270.4 2581.27   274.8 2581.12   306.1 2582.31   315.1 2582.18   345.9 2582.68
   363.7 2584.17   378.7 2587.77   389.5 2588.64   399.5 2590.21   406.4 2590.71
#Mann= 6 ,-1,0
       0     .06       0   47.93      .1       0   67.93     .06       0
   84.07    .045       0  104.64     .06       0  107.93     .05       0
Bank Sta=84.07,104.64
XS Rating Curve= 0 ,0
Exp/Cntr=0.3,0.1

Type RM Length L Ch R = 1 ,24901   ,178.3,180.3,180.3
XS GIS Cut Line= 2
2279640.30716039481229.1448953122279892.09961975480987.792611094
#Sta/Elev= 30
       0 2597.78      14 2596.99    16.9 2596.61    19.7 2595.49      22 2594.36
    25.3 2592.13    33.8 2585.27    40.4 2580.74    45.1 2578.18    50.8  2576.1
    56.5 2575.04    67.8 2575.09    79.1 2574.07    88.5 2573.12    93.2 2574.08
    96.1 2575.21    99.6 2575.95   110.6 2574.38   144.5  2577.1     166 2577.36
   188.2 2578.59   203.6 2578.54   232.5 2579.99   254.5 2578.87   276.9 2578.94
   293.5 2579.81   305.4 2581.04   319.6 2581.39   332.3  2583.2   348.8 2584.69
#Mann= 5 ,-1,0
       0      .1       0      30     .06       0    79.1    .045       0
    93.2     .06       0     170     .05       0
Bank Sta=79.1,93.2
XS Rating Curve= 0 ,0
Exp/Cntr(USF)=0,0
Exp/Cntr=0.3,0.1

Type RM Length L Ch R = 1 ,24721   ,235.2,233,226.4
XS GIS Cut Line= 3
2279737.19623492481359.7513266912279940.00159982481186.770066785
2279995.08990456481068.367135292
#Sta/Elev= 30
       0 2593.16    16.3 2592.78    24.9 2592.13    29.5 2591.07    32.3 2589.76
    35.5 2587.76    40.9 2582.79    53.3 2573.06   55.76  2571.4    57.8  2570.7
    61.7 2570.41    66.4 2570.57    70.9 2571.41    77.5 2572.84    82.8 2573.27
   108.9 2573.19   130.1 2572.31   166.9 2574.16   193.2 2573.17   224.7 2573.82
   240.5 2573.52   256.5 2574.57   266.6 2575.63   276.4 2576.04   290.4 2576.16
   299.2 2575.57   337.1 2577.41   378.6 2583.09   391.8 2584.52   397.1  2584.7
#Mann= 4 ,-1,0
       0     .06       0   55.76    .045       0    70.9     .06       0
      80     .05       0
#XS Ineff= 2 , 0
                          167.89         2576.34
Permanent Ineff=
       F       F
Bank Sta=55.76,70.9
XS Rating Curve= 0 ,0
Exp/Cntr=0.3,0.1

Type RM Length L Ch R = 1 ,24488   ,215.4,214.6,211.6
XS GIS Cut Line= 2
2279876.74642101481491.9916577682280124.85411267481173.873379842
#Sta/Elev= 30
       0 2587.07     8.6 2586.59      13 2585.88    15.8 2584.29    30.1 2574.31
    32.9    2573    35.8 2572.52    44.6  2571.8    54.3 2572.38      70 2571.86
    84.7 2572.05    95.6  2571.2   112.7 2571.43   121.3 2569.86   132.7    2570
   135.7 2569.83   142.2  2568.6   152.6 2568.45   160.8 2567.89   165.9 2568.52
   175.4 2570.15   186.2 2570.76   201.4 2570.97   233.2 2570.51   263.8 2571.57
   278.7 2571.73   289.4 2572.46   326.5 2573.08   350.3 2575.78   403.4  2580.6
#Mann= 3 ,-1,0
       0     .05       0   152.6    .045       0   165.9     .05       0
#XS Ineff= 2 , 0
          111.55 2573.17
Permanent Ineff=
       F       F
Bank Sta=152.6,165.9
XS Rating Curve= 0 ,0
Exp/Cntr(USF)=0,0
Exp/Cntr=0.3,0.1

Type RM Length L Ch R = 1 ,24273   ,176.8,180.6,181.3
XS GIS Cut Line= 3
2280031.50666432481636.9258538892280218.20156102481347.057461647
 2280258.7340057481242.655710204
#Sta/Elev= 30
       0 2581.01     8.6  2580.5    17.7 2578.28    23.4 2577.38    42.5 2576.74
    61.1 2574.85    71.1 2574.28    80.6 2573.17     112 2570.89     145 2569.35
   175.7 2568.69   185.5 2567.61   191.3 2567.54   199.5 2566.43   215.5 2566.71
   218.6 2566.64  221.472566.051   228.1 2565.51  230.472566.072   234.7 2567.05
   266.1 2567.21   275.7 2568.28   292.6 2567.78   318.5 2567.62     328 2568.69
   342.3 2571.17     357 2572.79   383.4 2575.09   416.6 2577.21   456.8 2581.14
#Mann= 4 ,-1,0
       0     .06       0      40     .05       0  221.47    .045       0
  230.47     .05       0
#XS Ineff= 2 , 0
          188.94 2570.09
Permanent Ineff=
       F       F
Bank Sta=221.47,230.47
XS Rating Curve= 0 ,0
Exp/Cntr(USF)=0,0
Exp/Cntr=0.3,0.1

Type RM Length L Ch R = 1 ,24092   ,243.7,254.9,260
XS GIS Cut Line= 4
2280122.26960619481744.9943492382280219.52777778481646.896504577
2280329.92986186481478.1979929182280393.02104352481287.583947564
#Sta/Elev= 30
       0 2576.19     9.7 2575.76    19.8 2571.36    25.4  2570.1    67.3 2569.62
    94.6 2568.11   122.8  2567.2   139.3 2567.23   148.5  2566.6   203.4 2566.66
   216.7 2565.65   234.3 2566.31   241.6 2565.85     274 2566.88   278.5 2566.67
   287.2 2565.05   297.9 2565.33   304.5  2564.8     319 2564.38  327.872564.797
   340.8 2565.83   353.5 2565.09   361.9 2566.23   374.5 2566.01   378.7 2566.61
   399.3 2571.94     404 2572.64     488 2577.28     522 2579.76   540.5 2582.81
#Mann= 7 ,-1,0
       0     .06       0      60     .05       0      70     .06       0
  188.14     .05       0   304.5    .045       0  327.87     .05       0
  449.75      .1       0
#XS Ineff= 2 , 0
          204.51 2568.83
Permanent Ineff=
       F       F
Bank Sta=304.5,327.87
XS Rating Curve= 0 ,0
Exp/Cntr=0.3,0.1

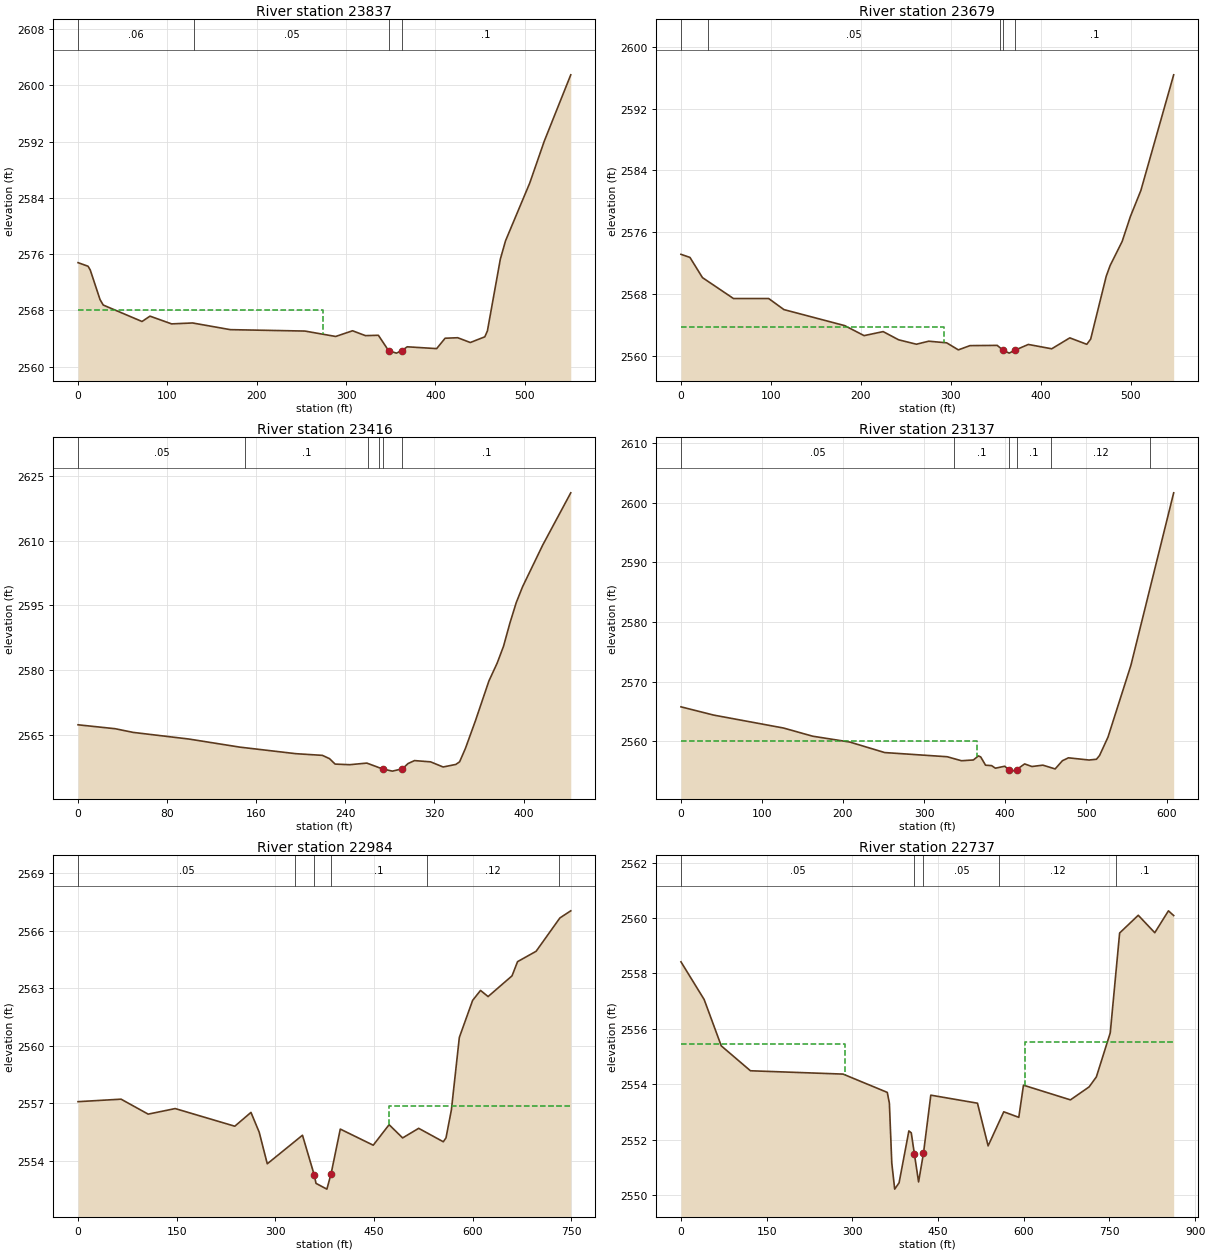
Type RM Length L Ch R = 1 ,23837   ,166.3,158.7,144.9
XS GIS Cut Line= 3
2280159.24527786481791.0719692542280559.65670104 481542.35014964
2280613.69996061481483.393866473
#Sta/Elev= 30
       0 2574.78    11.2 2574.27    13.7 2573.72    24.6 2569.53    28.2 2568.75
    71.6 2566.41    80.5 2567.17   104.7 2566.07   128.2  2566.2   170.4 2565.25
   253.8 2565.05   288.3 2564.28   307.2 2565.09   321.6  2564.4   336.1 2564.45
   347.7 2562.23   356.4 2561.91   362.2 2562.26   368.4 2562.81   401.3 2562.55
   410.8 2564.03   424.9  2564.1     439 2563.42   455.2 2564.23   458.1 2565.06
   472.6 2575.29   478.4 2577.89   505.5 2586.11   521.8 2592.08   551.4  2601.5
#Mann= 4 ,-1,0
       0     .06       0     130     .05       0   347.7    .045       0
   362.2      .1       0
#XS Ineff= 2 , 0
          274.65 2568.09
Permanent Ineff=
       F       F
Bank Sta=347.7,362.2
XS Rating Curve= 0 ,0
Exp/Cntr(USF)=0,0
Exp/Cntr=0.3,0.1

Type RM Length L Ch R = 1 ,23679   ,255.4,263.2,264.7
XS GIS Cut Line= 3
2280349.88250078 481996.635709492280533.34301626481792.511320399
2280637.65095064481539.893637842
#Sta/Elev= 30
       0 2573.17      10 2572.77    23.9 2570.16    58.4 2567.46    97.5 2567.46
   114.5 2566.03   182.1 2563.96   203.6 2562.67   224.8 2563.19     242 2562.13
   261.8 2561.56   275.4 2561.95   295.4 2561.74   308.4 2560.83   321.3 2561.38
   351.6 2561.41  357.97  2560.8   364.9 2560.41   371.2 2560.78   386.2 2561.53
   412.2 2560.97   432.3 2562.38   451.2 2561.55   455.5 2562.22   472.8 2570.34
   477.1 2571.71   490.5 2574.83   499.7 2578.06   511.3 2581.41   547.8 2596.35
#Mann= 5 ,-1,0
       0     .06       0      30     .05       0  354.45      .1       0
  357.97    .045       0   371.2      .1       0
#XS Ineff= 2 , 0
          292.39 2563.77
Permanent Ineff=
       F       F
Bank Sta=357.97,371.2
XS Rating Curve= 0 ,0
Exp/Cntr=0.3,0.1

Type RM Length L Ch R = 1 ,23416   ,283.4,278.7,273.4
XS GIS Cut Line= 2
2280603.87391341482016.4569267812280872.86195537481665.175739573
#Sta/Elev= 30
       0 2567.36    33.4 2566.45    49.5  2565.6    99.6 2564.06   145.2 2562.19
   195.6 2560.67   219.4 2560.28   225.8 2559.52   230.8 2558.26   243.9 2558.12
   259.3 2558.49   273.6 2557.12   282.2 2556.63   291.3 2557.17   296.3 2558.39
   302.1 2559.07   316.5 2558.78   327.8 2557.59   339.2 2558.18   342.6 2558.79
   347.8 2561.88   356.8 2568.29   368.9 2577.51   376.3 2581.64     382 2585.53
   387.7 2590.87   393.4 2595.63   399.1 2599.32   417.2 2608.98   442.4 2621.09
#Mann= 6 ,-1,0
       0     .05       0     150      .1       0     260     .05       0
     270      .1       0   273.6    .045       0   291.3      .1       0
Bank Sta=273.6,291.3
XS Rating Curve= 0 ,0
Exp/Cntr(USF)=0,0
Exp/Cntr=0.3,0.1

Type RM Length L Ch R = 1 ,23137   ,155.2,153.1,149
XS GIS Cut Line= 4
2280739.66283964482127.9082175092280939.13292269481982.068476081
2281051.36231832481767.5774555142280968.35956741481682.330998787
#Sta/Elev= 30
       0  2565.8    40.3 2564.42   126.6 2562.25   162.6 2560.88   208.4  2559.9
   251.5 2558.14   328.6 2557.44   346.3 2556.77     361  2556.9   367.1 2557.58
     370 2557.41     376 2556.02   383.5 2555.95   388.1 2555.52   399.7 2555.85
   404.6 2555.25   408.6 2555.03   414.5 2555.29   424.2 2556.24   433.2  2555.8
   446.7 2556.03   461.9  2555.4   470.8 2556.77   478.3 2557.26   503.7 2556.89
   512.9 2557.02   516.7 2557.65   527.1 2560.72   555.4 2572.76   608.2 2601.65
#Mann= 6 ,-1,0
       0     .05       0   337.1      .1       0   404.6    .045       0
   414.5      .1       0   457.1     .12       0  579.18      .1       0
#XS Ineff= 2 , 0
          365.75 2560.03
Permanent Ineff=
       F       F
Bank Sta=404.6,414.5
XS Rating Curve= 0 ,0
Exp/Cntr=0.3,0.1

Type RM Length L Ch R = 1 ,22984   ,243.5,246.8,254.6
XS GIS Cut Line= 3
2281054.26436273482220.7556078672281189.05239009 481665.69102297
2281170.33183073481488.781737058
#Sta/Elev= 30
       0 2557.08    65.4 2557.21   106.6 2556.43   147.7 2556.72   238.3  2555.8
   262.9 2556.52   275.4 2555.49   287.7 2553.84   341.2 2555.33   358.9 2553.28
   361.8 2552.82   378.3 2552.52  384.64 2553.31   398.7 2555.65   448.8 2554.81
   472.9 2555.88   493.5 2555.19   517.9 2555.69   555.3 2554.99   559.4 2555.19
   567.6 2556.65   579.7 2560.43   599.9 2562.36   611.9 2562.88   623.4 2562.56
   659.8 2563.64   668.2 2564.38   696.4 2564.92   732.6 2566.66   749.1 2567.03
#Mann= 6 ,-1,0
       0     .05       0     330      .1       0   358.9    .045       0
  384.64      .1       0     530     .12       0   731.2      .1       0
#XS Ineff= 2 , 0
                           472.5         2556.84
Permanent Ineff=
       F       F
Bank Sta=358.9,384.64
XS Rating Curve= 0 ,0
Exp/Cntr(USF)=0,0
Exp/Cntr=0.3,0.1

Type RM Length L Ch R = 1 ,22737   ,371.3,383.7,383
XS GIS Cut Line= 4
2281138.32521067482423.2661261582281303.96009135481975.702412677
2281339.58250395481835.9682806642281286.78903096 481600.90585629
#Sta/Elev= 30
       0 2558.42    40.6 2557.06    70.5 2555.39   121.6 2554.49   283.7 2554.37
   361.1 2553.71   364.8 2553.32     369 2551.16   374.1 2550.22   381.8 2550.45
   398.9 2552.32   403.1 2552.25   408.7 2551.47   415.9 2550.48   424.5 2551.52
   437.3 2553.61     519 2553.32   537.6 2551.78     565 2553.01   591.3 2552.81
   599.5 2553.97   681.7 2553.44   714.5 2553.91   727.1 2554.27   751.4 2555.86
   767.8 2559.46   800.4  2560.1   829.3 2559.47   853.2 2560.26   862.4 2560.09
#Mann= 5 ,-1,0
       0     .05       0   408.7    .045       0   424.5     .05       0
  557.23     .12       0  761.43      .1       0
#XS Ineff= 2 , 0
          286.76 2555.46  601.69         2555.53
Permanent Ineff=
       F       F
Bank Sta=408.7,424.5
XS Rating Curve= 0 ,0
Exp/Cntr=0.3,0.1

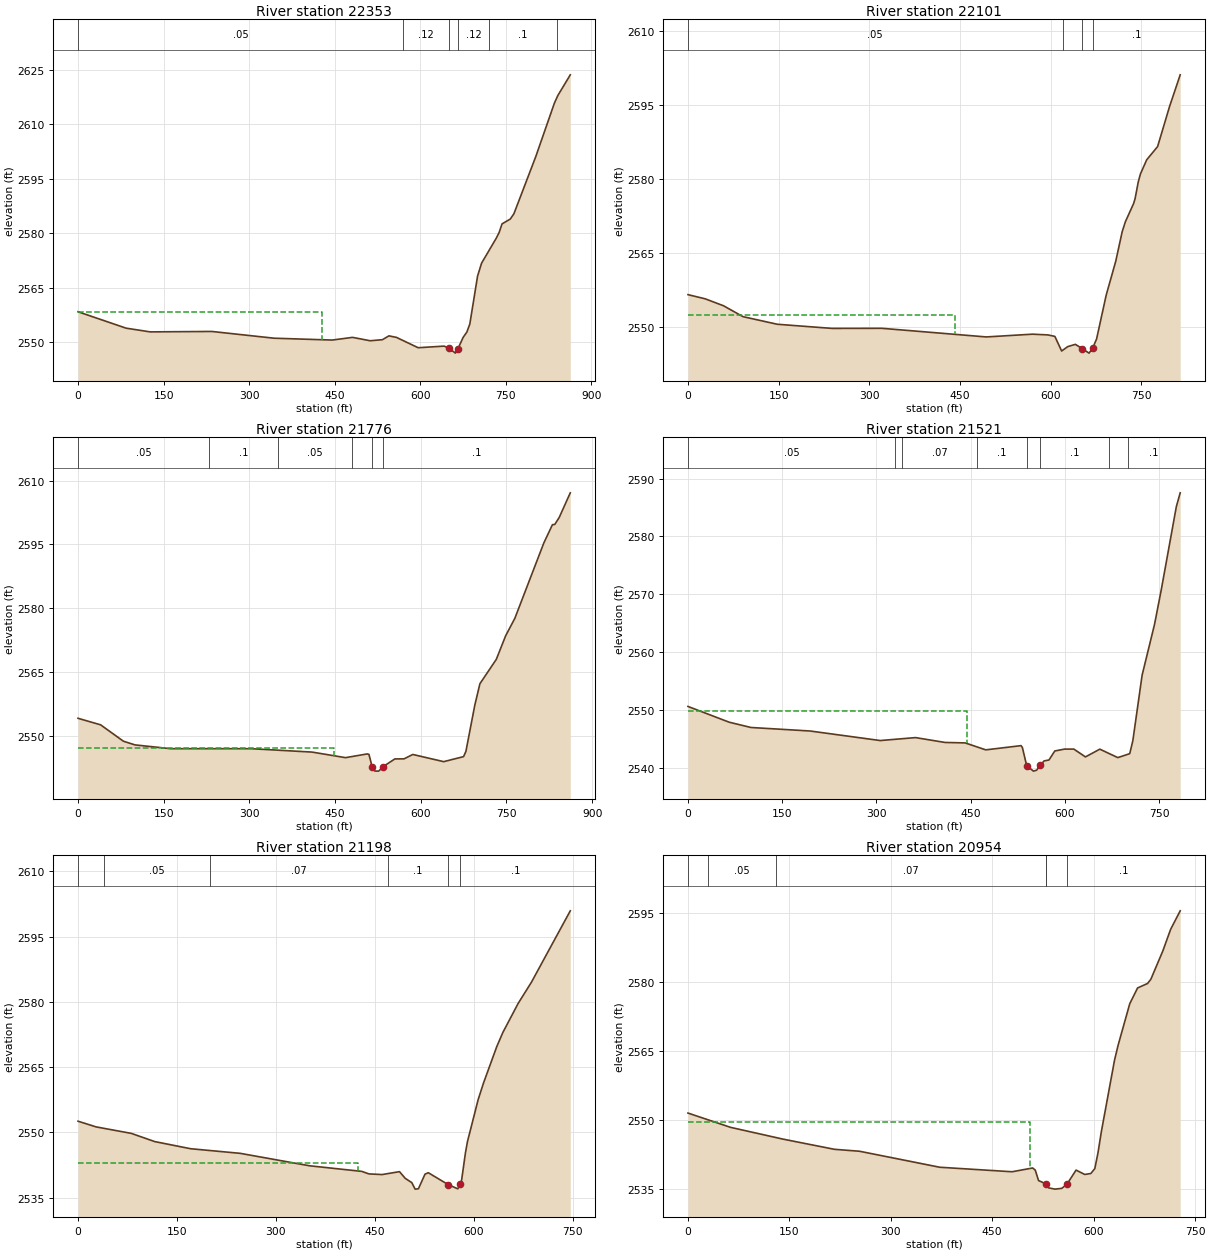
Type RM Length L Ch R = 1 ,22353   ,248,252.8,254.7
XS GIS Cut Line= 2
2281188.33207227482455.6857878912281730.17542262481784.159550371
#Sta/Elev= 30
       0 2558.34    84.2 2553.82   126.6 2552.79   234.5 2552.91   343.7 2551.05
   445.6 2550.54   481.2 2551.28   512.1 2550.35   533.6 2550.64     545  2551.7
   558.3 2551.27   596.2 2548.43   641.7 2548.87   650.8 2548.25   661.6 2546.94
   666.2 2548.21     675 2551.25   681.7 2552.77   686.8 2554.95   700.4 2568.16
   707.4 2571.72   733.1 2578.58   738.2 2580.17   743.3 2582.55   757.8 2583.88
   764.1 2585.33   802.4 2601.07   835.1 2615.82     841 2617.87   862.9  2623.6
#Mann= 6 ,-1,0
       0     .05       0     570     .12       0   650.8    .045       0
   666.2     .12       0     720      .1       0     840     .05       0
#XS Ineff= 2 , 0
          427.04 2558.38
Permanent Ineff=
       F       F
Bank Sta=650.8,666.2
XS Rating Curve= 0 ,0
Exp/Cntr(USF)=0,0
Exp/Cntr=0.3,0.1

Type RM Length L Ch R = 1 ,22101   ,320.7,324.2,322.1
XS GIS Cut Line= 2
2281278.29735523482539.8199559272281892.53001632482004.759534589
#Sta/Elev= 30
       0 2556.51    28.4 2555.67    58.8 2554.26    91.1 2552.05   147.8 2550.51
   238.5 2549.67   320.8 2549.69   493.7 2547.94   570.2  2548.5   595.7 2548.35
   607.2 2548.05   618.4 2545.09   628.5 2545.98   641.1 2546.44   652.4 2545.58
   663.8 2544.66  669.582545.634   676.2 2547.52   692.1  2556.4     708 2563.31
   718.6 2569.27   723.9 2571.29   737.5 2574.97   739.9 2575.94   745.2 2579.36
   748.8 2580.97   759.2 2583.84   777.2 2586.51     797 2594.64   814.6 2601.05
#Mann= 4 ,-1,0
       0     .05       0     620      .1       0   652.4    .045       0
  669.58      .1       0
#XS Ineff= 2 , 0
           442.4 2552.35
Permanent Ineff=
       F       F
Bank Sta=652.4,669.58
XS Rating Curve= 0 ,0
Exp/Cntr=0.3,0.1

Type RM Length L Ch R = 1 ,21776   ,252,255.7,254.2
XS GIS Cut Line= 3
2281470.26130014482726.8904737792281996.41614324482306.590663737
2282036.62042664482122.669806973
#Sta/Elev= 30
       0  2554.1    39.6 2552.56    79.4 2548.71    99.7 2547.84     162 2546.95
   304.3 2546.94   409.6 2546.15   468.3 2544.84   506.3 2545.72   509.3 2545.61
  514.872542.688   519.5 2541.69   526.3 2541.67 534.051 2542.74   554.7 2544.54
   570.7 2544.56     586 2545.59   640.1  2543.9   674.9 2545.08     679 2546.31
   694.6  2557.2   703.5 2562.23   732.2 2567.96   748.6 2573.52   764.7 2577.63
   815.5 2595.38   830.5 2599.65   834.5 2599.69   842.4 2601.36   861.7 2607.14
#Mann= 6 ,-1,0
       0     .05       0     230      .1       0     350     .05       0
     480      .1       0  514.87    .045       0 534.051      .1       0
#XS Ineff= 2 , 0
          448.33 2547.19
Permanent Ineff=
       F       F
Bank Sta=514.87,534.051
XS Rating Curve= 0 ,0
Exp/Cntr=0.3,0.1

Type RM Length L Ch R = 1 ,21521   ,320,323.1,320.7
XS GIS Cut Line= 2
2281570.96078887482883.2541188552282205.25134591482423.586063344
#Sta/Elev= 30
       0  2550.6    65.7 2547.87   100.3 2546.96   194.4 2546.35     306  2544.7
   362.1 2545.21   409.1 2544.37   441.2 2544.29   473.9 2543.09   530.1 2543.82
   532.2 2543.49  539.02 2540.35   549.8 2539.41   554.8 2539.57   560.6  2540.4
   566.6 2541.17   574.5 2541.34   583.8  2542.9   599.2 2543.22   614.1 2543.22
   632.5 2541.87   655.4 2543.21     684 2541.75     703 2542.43   707.9 2544.65
   722.7 2556.01   742.5 2564.82   753.4 2570.91   777.1 2585.14   783.3 2587.55
#Mann= 8 ,-1,0
       0     .05       0     330      .1       0     340     .07       0
     460      .1       0  539.02    .045       0   560.6      .1       0
     670     .12       0     700      .1       0
#XS Ineff= 2 , 0
          443.63 2549.85
Permanent Ineff=
       F       F
Bank Sta=539.02,560.6
XS Rating Curve= 0 ,0
Exp/Cntr(USF)=0,0
Exp/Cntr=0.3,0.1

Type RM Length L Ch R = 1 ,21198   ,243.6,243.5,240
XS GIS Cut Line= 3
2281759.68406876483103.0733746162282229.24429749482750.127969595
2282386.53839093482728.164371967
#Sta/Elev= 30
       0 2552.55    27.4 2551.24    80.7 2549.75   116.3 2547.86   170.7 2546.22
   245.8 2545.16   350.9  2542.3   430.2 2541.01     441 2540.43     461 2540.28
   487.3 2540.95     496 2539.41     506 2538.42     511 2536.93     516 2537.01
     526 2540.38     531  2540.7   561.1 2537.97   575.7    2537   579.52538.025
   581.6 2539.13   587.3 2545.28   590.4 2547.89   606.5 2557.48   614.6  2561.3
   634.8 2569.71     644 2572.95   667.1 2579.61   687.3  2584.5   746.2 2600.92
#Mann= 6 ,-1,0
       0     .07       0      40     .05       0     200     .07       0
     470      .1       0   561.1    .045       0   579.5      .1       0
#XS Ineff= 2 , 0
          425.07 2542.95
Permanent Ineff=
       F       F
Bank Sta=561.1,579.5
XS Rating Curve= 0 ,0
Exp/Cntr=0.3,0.1

Type RM Length L Ch R = 1 ,20954   ,138.3,146,152.8
XS GIS Cut Line= 3
 2281818.7410265483172.5645192312282226.70508366483040.489824468
2282471.77701728482868.792721277
#Sta/Elev= 30
       0  2551.5    62.9  2548.4   140.3 2545.85   216.6 2543.63   253.8 2543.21
   372.3 2539.74   479.4 2538.76   509.8 2539.58   513.6 2539.12   518.5 2536.85
   529.9  2536.1   533.2 2535.27   542.9 2534.99   552.9 2535.16  560.62 2536.08
     574 2539.12   586.9 2538.17   595.9 2538.39   601.7 2539.44   606.4 2542.85
   611.3 2547.39   630.8 2562.92   636.1 2566.18   653.4 2575.22     665 2578.65
   679.7 2579.61   684.6 2580.53   702.2 2586.64   713.9 2591.38     728 2595.38
#Mann= 6 ,-1,0
       0     .07       0      30     .05       0     130     .07       0
  528.81      .1       0   529.9    .045       0  560.62      .1       0
#XS Ineff= 2 , 0
          505.26 2549.51
Permanent Ineff=
       F       F
Bank Sta=529.9,560.62
XS Rating Curve= 0 ,0
Exp/Cntr(USF)=0,0
Exp/Cntr=0.3,0.1

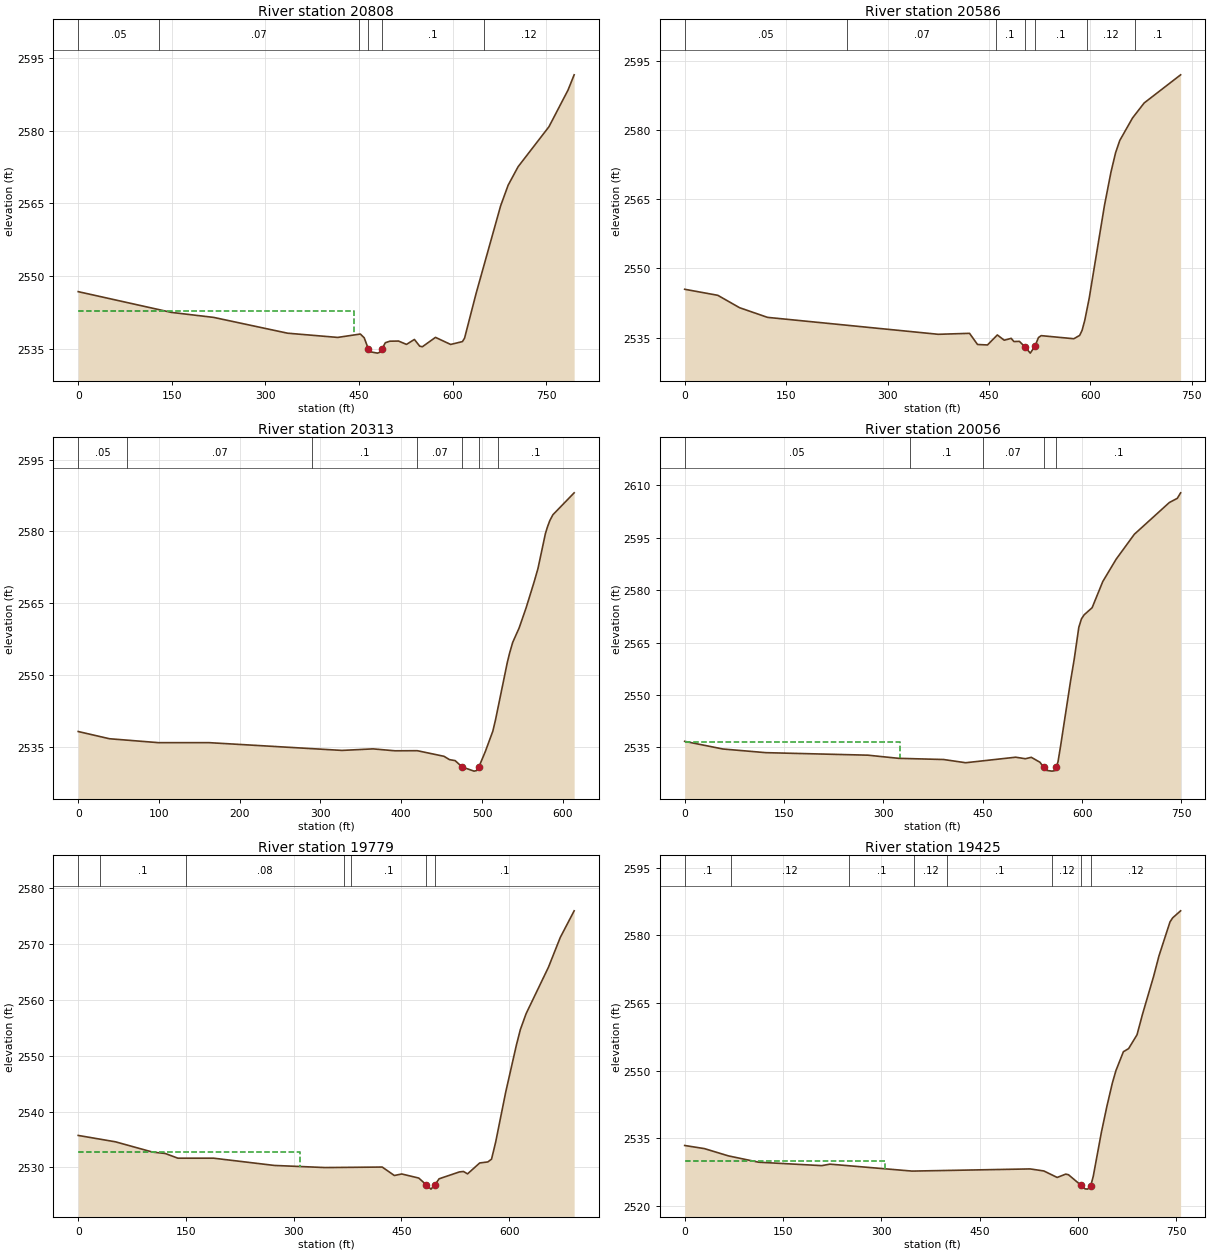
Type RM Length L Ch R = 1 ,20808   ,218,222.1,222.8
XS GIS Cut Line= 3
2281915.06983601483267.1668244352282531.38454731483054.024653444
 2282673.9073243483056.592631408
#Sta/Elev= 30
       0 2546.78   149.3  2542.5     217 2541.47   335.5 2538.21   415.9 2537.34
   452.1 2538.04   458.3 2537.26   464.7 2535.04   467.9 2534.38   479.4  2534.1
   483.7 2534.29   486.7 2534.95   492.1 2536.24   499.3 2536.56   513.3 2536.59
     526  2535.9   538.7 2536.92   547.2 2535.54   551.4 2535.41   572.5 2537.35
   596.8 2535.89   615.7 2536.48   619.1 2537.19   637.7 2546.47   676.9 2564.48
   688.9 2568.73   704.9 2572.55   754.3 2580.79   784.9 2588.36   794.7  2591.5
#Mann= 6 ,-1,0
       0     .05       0     130     .07       0     450      .1       0
   464.7    .045       0   486.7      .1       0     650     .12       0
#XS Ineff= 2 , 0
          441.26 2542.87
Permanent Ineff=
       F       F
Bank Sta=464.7,486.7
XS Rating Curve= 0 ,0
Exp/Cntr(USF)=0,0
Exp/Cntr=0.3,0.1

Type RM Length L Ch R = 1 ,20586   ,272.9,273.5,260.3
XS GIS Cut Line= 4
2282029.48917806 483524.301252522282434.90314353483295.766139504
2282563.89576691483280.2998422112282696.60986964483242.346757791
#Sta/Elev= 30
       0 2545.48      49 2544.17    81.1 2541.49   122.5 2539.39     375 2535.72
   421.2 2535.93     433 2533.51   447.7 2533.41   462.3 2535.58   472.5 2534.44
   482.8 2534.84   486.8 2534.15   494.9 2534.19502.68172533.067     511 2531.64
  517.872533.116   523.1 2535.01   527.1 2535.43   575.4 2534.76     584 2535.48
   587.6 2536.57   591.6 2538.76   598.1  2543.5   620.7 2563.65   630.4 2570.93
   637.2  2575.1   643.3 2577.72   662.2 2582.61   679.4 2585.86   733.3 2591.96
#Mann= 7 ,-1,0
       0     .05       0     240     .07       0     460      .1       0
502.6817    .045       0  517.87      .1       0  595.31     .12       0
  665.31      .1       0
Bank Sta=502.6817,517.87
XS Rating Curve= 0 ,0
Exp/Cntr=0.3,0.1

Type RM Length L Ch R = 1 ,20313   ,252.1,256.6,255.6
XS GIS Cut Line= 2
2282186.90309001483692.140943686  2282714.765227483378.276970339
#Sta/Elev= 30
       0 2538.14    38.7 2536.63    99.4 2535.81   162.3 2535.81   326.7 2534.19
     365 2534.51   392.4 2534.11   419.9 2534.13   452.9 2532.96   459.7 2532.27
   466.8 2532.05   475.4 2530.73   490.1 2529.86   493.4 2529.98  496.032530.701
   504.1 2533.95   513.4 2538.21   516.7 2540.56   531.3 2552.55   534.2 2554.55
     538 2556.77     546  2559.8   554.7 2564.04   564.6 2569.45   569.3 2572.22
   578.5 2579.51   580.9 2580.84   583.9 2582.21   587.8 2583.46   614.1 2588.04
#Mann= 7 ,-1,0
       0     .05       0      60     .07       0     290      .1       0
     420     .07       0   475.4    .045       0  496.03     .07       0
     520      .1       0
Bank Sta=475.4,496.03
XS Rating Curve= 0 ,0
Exp/Cntr(USF)=0,0
Exp/Cntr=0.3,0.1

Type RM Length L Ch R = 1 ,20056   ,276.5,277.1,271.1
XS GIS Cut Line= 3
2282237.58196327 483888.76569952  2282756.311596483605.048654424
2282913.16221199483589.835031769
#Sta/Elev= 30
       0 2536.75    57.5 2534.57   122.4 2533.52   276.5  2532.8   322.9  2531.9
   390.9 2531.56   424.3 2530.64   499.9 2532.22   514.4 2531.78   523.3 2532.19
   536.4 2530.78  542.112529.335   545.5 2528.47   554.6 2528.24   559.2 2528.38
     561 2529.34   563.7 2530.93   567.5 2535.32   582.6 2553.97   588.1 2560.18
   595.1 2569.36   599.1 2571.78   603.2 2572.94   615.2 2574.96   631.3 2582.45
   651.4 2588.81   678.9 2595.95   731.8 2605.03   743.8 2606.23   748.8  2607.8
#Mann= 5 ,-1,0
       0     .05       0     340      .1       0     450     .07       0
  542.11    .045       0     561      .1       0
#XS Ineff= 2 , 0
          325.41 2536.58
Permanent Ineff=
       F       F
Bank Sta=542.11,561
XS Rating Curve= 0 ,0
Exp/Cntr=0.3,0.1

Type RM Length L Ch R = 1 ,19779   ,346.4,353.7,363.1
XS GIS Cut Line= 3
2282308.16871607484160.0835948582282646.28581463483950.365394485
2282853.15070616483743.500502961
#Sta/Elev= 30
       0 2535.73    51.8 2534.59   103.8 2532.74   121.2  2532.5   138.7 2531.66
   188.3 2531.66     273 2530.36   343.6 2529.98   423.2 2530.07   440.1 2528.56
   450.5 2528.83   474.1  2528.1   484.4 2526.91   491.1 2526.12   496.7 2526.91
   502.4 2527.97   530.7  2529.2   536.3 2529.28     542 2528.85   558.9  2530.8
   570.3 2530.99   575.4 2531.49   581.1 2534.52   595.2 2543.53   609.9 2551.85
   615.5 2554.67   623.5 2557.52   654.6 2565.83   671.1 2571.17   690.4 2575.93
#Mann= 7 ,-1,0
       0     .12       0      30      .1       0     150     .08       0
     370     .07       0     380      .1       0   484.4    .045       0
   496.7      .1       0
#XS Ineff= 2 , 0
          308.41 2532.79
Permanent Ineff=
       F       F
Bank Sta=484.4,496.7
XS Rating Curve= 0 ,0
Exp/Cntr(USF)=0,0
Exp/Cntr=0.3,0.1

Type RM Length L Ch R = 1 ,19425   ,234.8,238.3,242.2
XS GIS Cut Line= 2
2282392.34132711484282.7758753482283115.65512023484061.644439581
#Sta/Elev= 30
       0 2533.43      30 2532.74    66.8 2531.12   112.8 2529.72     209 2528.96
   221.5 2529.29   346.8 2527.75   526.9 2528.23   547.8 2527.78   568.1 2526.34
   581.2 2527.08   585.4 2526.94  604.882524.559   610.5 2523.82   614.7 2523.75
   619.4 2524.55   623.1 2526.55   635.6 2536.38     644 2542.14   652.3 2547.29
   657.8 2550.06   669.1 2554.22   677.1 2554.92   689.9 2557.98   698.3 2562.55
   715.1 2570.88   723.4 2575.48   740.2 2583.01   744.3 2583.92   756.4 2585.47
#Mann= 8 ,-1,0
       0      .1       0      70     .12       0     250      .1       0
     350     .12       0     400      .1       0     560     .12       0
  604.88    .045       0   619.4     .12       0
#XS Ineff= 2 , 0
          305.33 2529.96
Permanent Ineff=
       F       F
Bank Sta=604.88,619.4
XS Rating Curve= 0 ,0
Exp/Cntr(USF)=0,0
Exp/Cntr=0.3,0.1