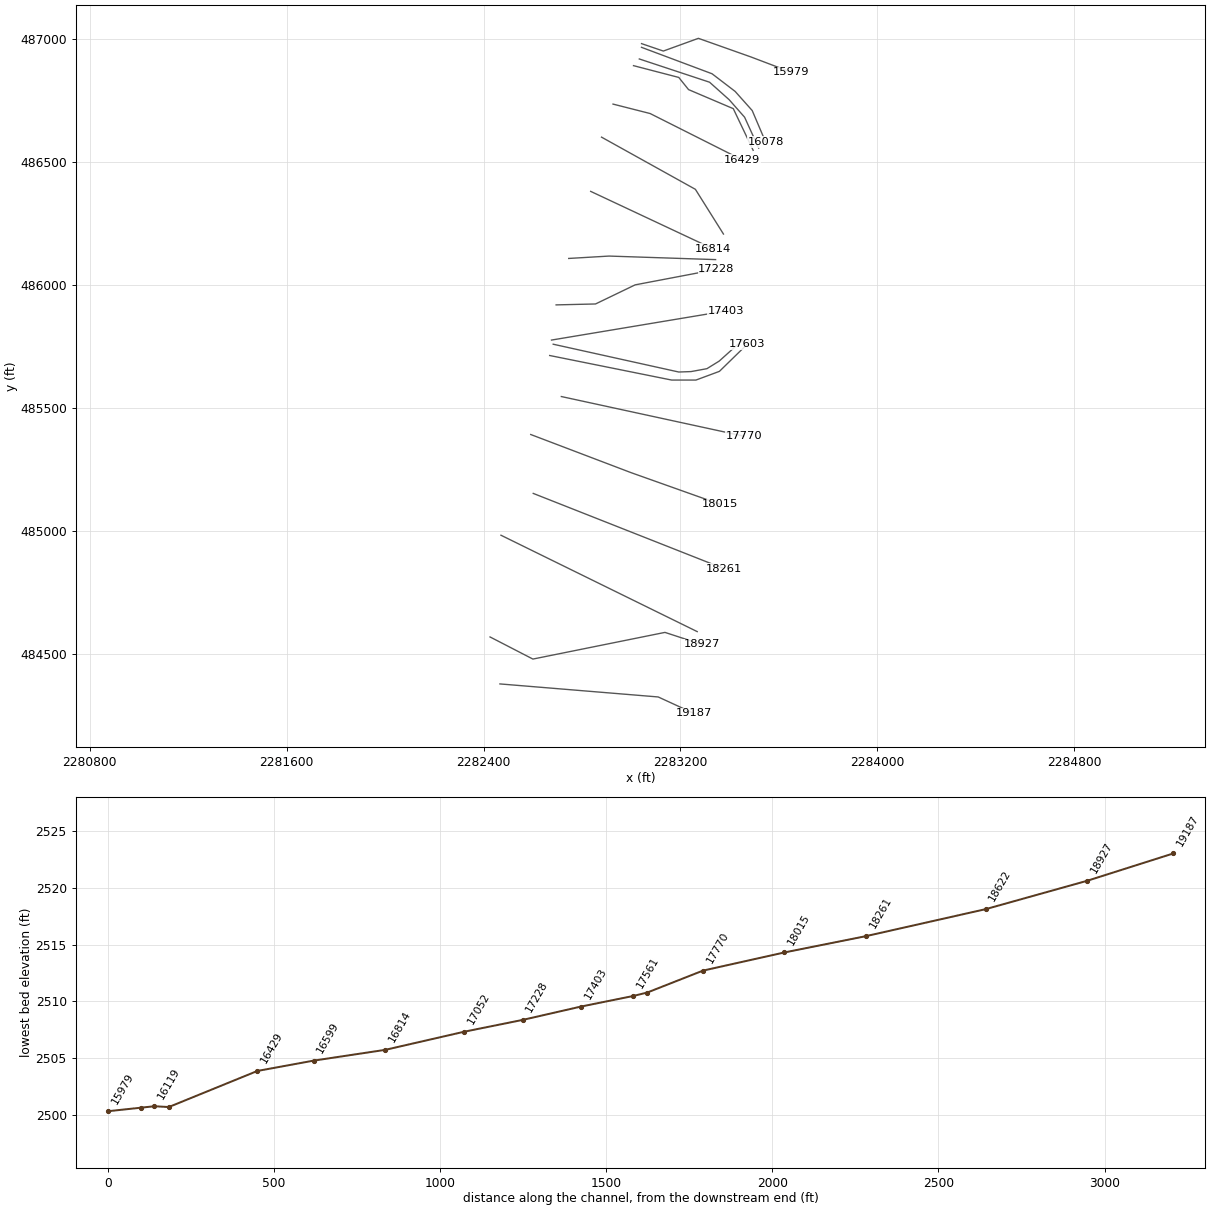
HEC-RAS study THOMASCK.prj: THOMASCK

--- THOMASCK.g01 (geometry) --- (continued)

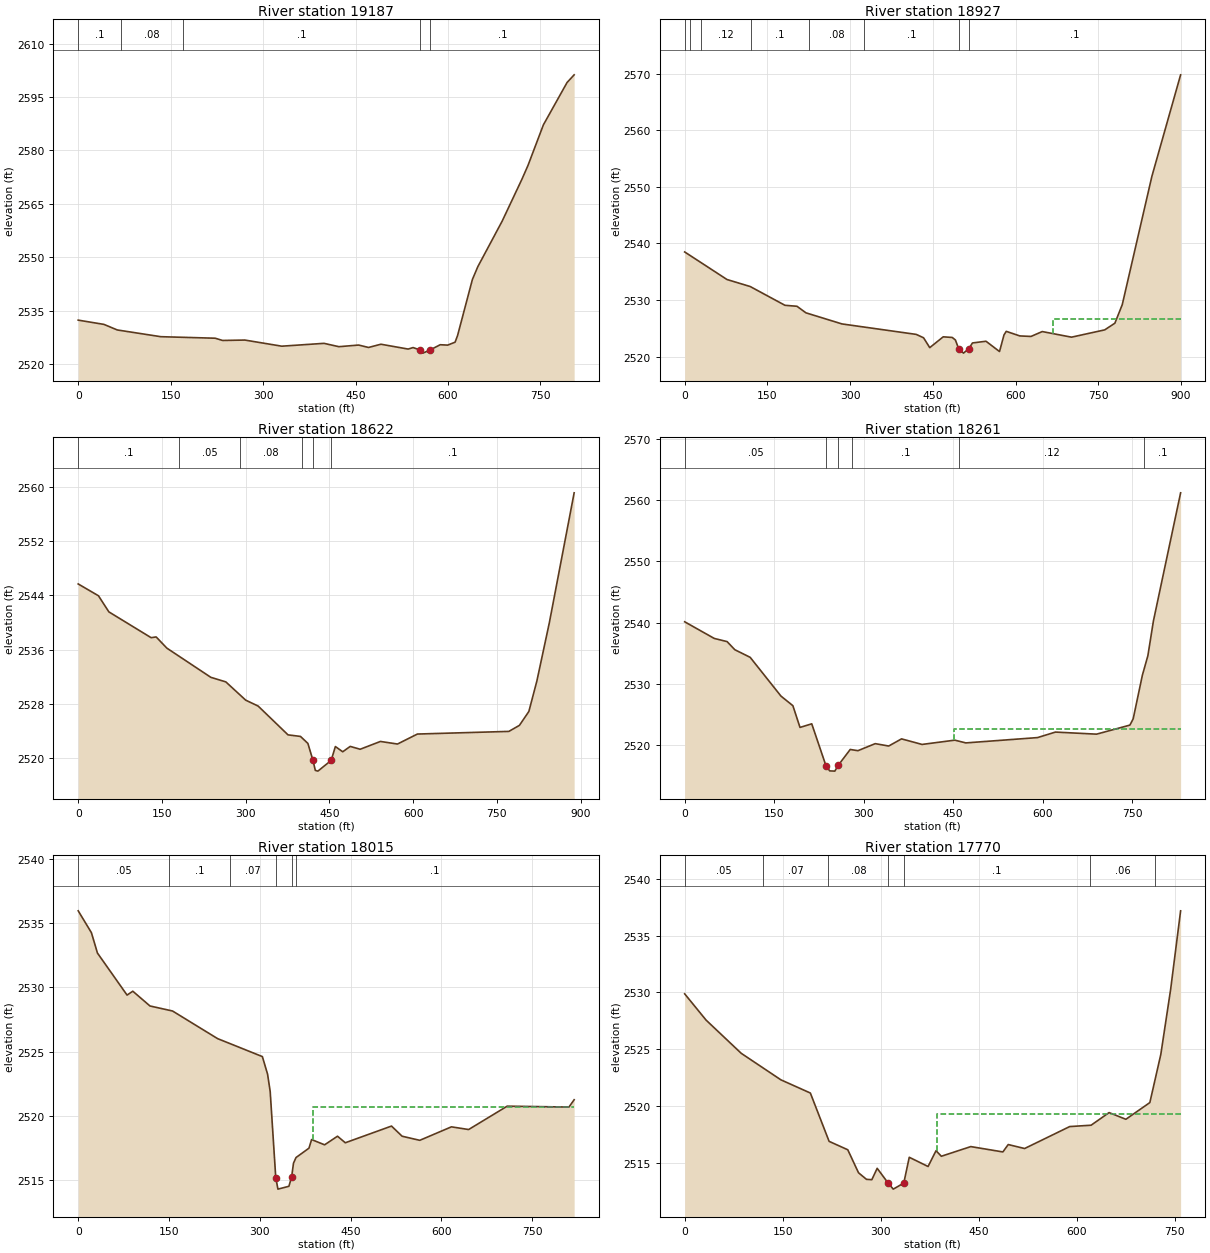
Type RM Length L Ch R = 1 ,19187   ,254.5,259.4,263.4
XS GIS Cut Line= 3
     2282466.628      484380.0562283109.66855261 484327.05988145
2283254.58741066484260.326504105
#Sta/Elev= 30
       0  2532.3    41.7 2531.11    63.4 2529.54     134 2527.65   222.3 2527.22
   234.3 2526.59   270.5  2526.7   330.4 2524.98   398.9 2525.78     423 2524.84
   455.1  2525.3   471.1 2524.62   491.2 2525.53   535.4 2524.17   543.4 2524.59
     554 2523.96   559.4 2523.03   571.5 2523.97   587.5 2525.39   599.6 2525.28
   611.6 2526.11   615.6 2527.96   639.7 2543.74   648.5 2547.33     688 2560.13
     720 2571.88   729.9 2575.78   754.9 2587.19   793.3 2599.08   804.8 2601.24
#Mann= 5 ,-1,0
       0      .1       0      70     .08       0     170      .1       0
     554    .045       0   571.5      .1       0
Bank Sta=554,571.5
XS Rating Curve= 0 ,0
Exp/Cntr=0.3,0.1

Type RM Length L Ch R = 1 ,18927   ,314.6,305.5,271.9
XS GIS Cut Line= 4
2282426.58103329484570.9600690572282600.63287306484481.080840326
2283137.05493659484589.5065765732283285.42699672484541.000326147
#Sta/Elev= 30
       0  2538.5    76.7 2533.63   118.8 2532.39   181.9 2529.07   203.6  2528.9
   219.9 2527.74   285.2 2525.78   419.9 2523.93   433.2 2523.33   444.4 2521.59
   468.8  2523.5   485.2 2523.39   490.9 2522.94   496.9 2521.39   505.6 2520.62
     515 2521.39   521.9 2522.42   546.4 2522.72   570.9  2520.9     579 2523.83
   583.1 2524.47   607.6 2523.66     628 2523.57   648.4 2524.43   701.5 2523.44
   761.7 2524.73   780.1 2525.91   793.5 2529.19   847.2 2551.86   899.3  2569.8
#Mann= 8 ,-1,0
       0     .12       0      10      .1       0      30     .12       0
     120      .1       0  225.89     .08       0  325.89      .1       0
   496.9    .045       0     515      .1       0
#XS Ineff= 2 , 0
                          667.04         2526.66
Permanent Ineff=
       F       F
Bank Sta=496.9,515
XS Rating Curve= 0 ,0
Exp/Cntr(USF)=0,0
Exp/Cntr=0.3,0.1

Type RM Length L Ch R = 1 ,18622   ,356.9,360.5,357.5
XS GIS Cut Line= 2
2282470.92368449484984.4700601282283268.10066109484592.668270416
#Sta/Elev= 30
       0 2545.68    36.3 2543.94    54.9 2541.57   130.6 2537.77   139.6 2537.88
   158.8 2536.23   237.6 2531.93   264.4 2531.26     300 2528.57   322.3  2527.7
   375.8 2523.46   398.1 2523.23   411.4  2522.2   420.4 2519.72   424.7 2518.23
   429.3 2518.12   453.12519.698   460.6 2521.74   473.8 2520.97   487.2 2521.76
     505 2521.34   541.3 2522.49   571.9 2522.11   607.5 2523.58   771.4 2523.97
   790.3 2524.86   807.2 2526.91   821.5 2531.38   843.8 2539.94   888.3  2559.1
#Mann= 6 ,-1,0
       0      .1       0     180     .05       0     290     .08       0
     400      .1       0   420.4    .045       0   453.1      .1       0
Bank Sta=420.4,453.1
XS Rating Curve= 0 ,0
Exp/Cntr=0.3,0.1

Type RM Length L Ch R = 1 ,18261   ,244.7,246,244.4
XS GIS Cut Line= 2
2282602.05952748485154.4617285982283375.30622545484849.157681797
#Sta/Elev= 30
       0 2540.14    49.6 2537.42    71.1  2536.9      84 2535.58   109.8 2534.33
   161.4    2528   181.4 2526.43   193.3 2522.88     213 2523.47   236.9  2516.6
   243.1 2515.78   251.7 2515.74   257.3 2516.68   277.5 2519.28   290.4 2519.08
   319.4 2520.23     342 2519.84   363.5 2521.01   397.9  2520.1   452.8  2520.8
   471.3 2520.35   591.5 2521.22   621.5 2522.12   690.4 2521.78   746.3 2523.26
   751.8 2524.29   767.2 2531.41   776.4 2534.59   785.7 2540.27   831.3 2561.21
#Mann= 6 ,-1,0
       0     .05       0   236.9    .045       0   257.3     .08       0
     280      .1       0     460     .12       0     770      .1       0
#XS Ineff= 2 , 0
                          451.41         2522.66
Permanent Ineff=
       F       F
Bank Sta=236.9,257.3
XS Rating Curve= 0 ,0
Exp/Cntr(USF)=0,0
Exp/Cntr=0.3,0.1

Type RM Length L Ch R = 1 ,18015   ,242.6,244.9,248.2
XS GIS Cut Line= 3
2282591.84351589485393.8864858212282998.68550085485239.106779638
     2283360.392      485110.393
#Sta/Elev= 30
       0 2535.97    21.8 2534.27    31.8 2532.68    80.7 2529.41    90.2 2529.71
   118.6 2528.56   155.8 2528.17   230.2 2526.02   304.2 2524.62   312.8 2523.25
   317.1 2521.91   326.3  2515.2   329.9  2514.3     348 2514.52   352.5 2515.24
   355.6 2516.32   359.8 2516.76   381.2 2517.49   385.5 2518.16     407 2517.75
   428.3 2518.42   441.2 2517.91   517.5 2519.21     535 2518.42   564.2  2518.1
   616.5 2519.15   644.9 2518.94   708.6 2520.76   810.6 2520.69   819.2 2521.26
#Mann= 6 ,-1,0
       0     .05       0     150      .1       0     250     .07       0
   326.3    .045       0   352.5     .07       0     360      .1       0
#XS Ineff= 2 , 0
                          387.37         2520.67
Permanent Ineff=
       F       F
Bank Sta=326.3,352.5
XS Rating Curve= 0 ,0
Exp/Cntr=0.3,0.1

Type RM Length L Ch R = 1 ,17770   ,166.6,167.6,166.7
BEGIN DESCRIPTION:
structure xs 4
END DESCRIPTION:
XS GIS Cut Line= 2
2282716.19188142485548.2183497062283458.05218206 485387.00639976
#Sta/Elev= 30
       0 2529.87    32.8 2527.56    86.6 2524.64   147.3 2522.31   192.4 2521.15
   221.1  2516.9   249.7 2516.16   266.1 2514.14   278.3 2513.56   286.5 2513.53
   294.7 2514.53   311.9  2513.2   319.3  2512.7   335.4 2513.23   343.8  2515.5
   372.6 2514.69   384.8 2516.08   392.9 2515.59     438 2516.44   487.1 2515.97
   495.3 2516.62   520.4 2516.27   589.4  2518.2   622.2 2518.32   649.7 2519.43
   675.4 2518.84   712.1 2520.31   728.9 2524.55   743.9 2530.25   759.2 2537.17
#Mann= 7 ,-1,0
       0     .05       0     120     .07       0     220     .08       0
   311.9    .045       0   335.4      .1       0     620     .06       0
     720      .1       0
#XS Ineff= 2 , 0
                          385.87         2519.32
Permanent Ineff=
       F       F
Bank Sta=311.9,335.4
XS Rating Curve= 0 ,0
Exp/Cntr(USF)=0,0
Exp/Cntr=0.5,0.3

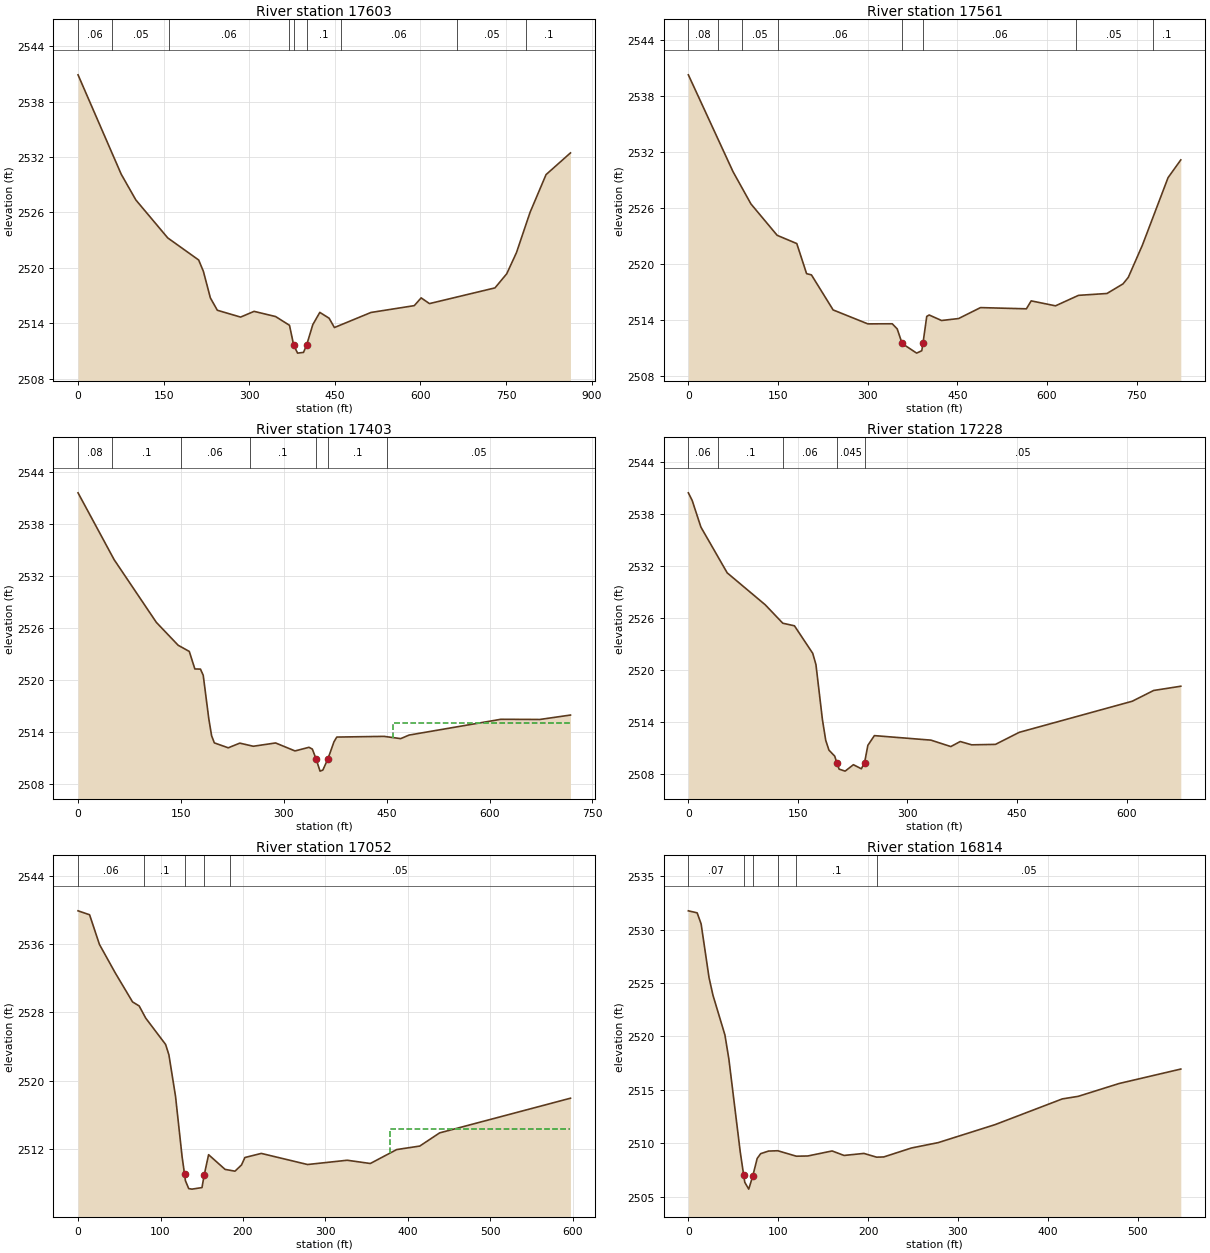
Type RM Length L Ch R = 1 ,17603   ,44,41.6,39
BEGIN DESCRIPTION:
structure xs 3
END DESCRIPTION:
XS GIS Cut Line= 5
2282668.83806689485715.0411257032283164.19469391485615.244003043
   2283263.08457485615.2440030432283358.34545981485650.626619259
2283470.84403444485760.403454184
#Sta/Elev= 30
       0 2540.89    75.7 2530.13   101.3 2527.35   157.2 2523.24   211.4 2520.85
   219.7 2519.62   231.9 2516.75   244.1 2515.41   284.9 2514.67   308.5 2515.29
   346.2 2514.73   370.6 2513.78     378 2511.61   384.8 2510.77   395.1 2510.85
   400.4  2511.6   411.4 2513.85   423.7 2515.18     440 2514.55   449.3 2513.54
   513.3 2515.17   589.3 2515.91   601.3 2516.75   615.9 2516.13   730.7 2517.83
   751.3 2519.36   768.3 2521.64   792.2 2526.01   820.2 2530.09     863 2532.44
#Mann= 9 ,-1,0
       0     .06       0      60     .05       0     160     .06       0
     370      .1       0     378    .045       0   400.4      .1       0
     460     .06       0   664.2     .05       0  785.82      .1       0
#XS Ineff= 2 , 0
           365.1 2512.36   413.3         2512.36
Permanent Ineff=
       F       F
Bank Sta=378,400.4
XS Rating Curve= 0 ,0
Exp/Cntr(USF)=0,0
Exp/Cntr=0.5,0.3

Type RM Length L Ch R = 1 ,17561   ,149,158.4,169.9
BEGIN DESCRIPTION:
structure xs 2
Bee Tree Road
END DESCRIPTION:
XS GIS Cut Line= 6
2282683.10205533485760.9309993932283193.22658414 485647.90487955
2283243.12514547485649.7193726892283307.53965191485661.513578094
2283357.43821324485692.359961462 2283452.0524578485777.391953404
#Sta/Elev= 30
       0 2540.24    74.8 2529.87   104.7 2526.43   148.6 2523.07   181.4 2522.19
   197.8 2518.97   205.9 2518.84   242.2 2515.09   300.2  2513.6   341.1 2513.61
   349.4 2513.06   357.6  2511.5   381.9 2510.47   390.5 2510.73  392.54 2511.54
   398.8  2514.4   402.9 2514.55   423.5 2513.96   452.1 2514.17   488.8 2515.34
   565.5 2515.21   573.5 2516.06   614.2 2515.53   652.7 2516.65   700.3 2516.85
   727.2 2517.88     736 2518.58   759.5 2522.01   802.5 2529.24   823.8 2531.14
#Mann= 8 ,-1,0
       0     .08       0      50      .1       0      90     .05       0
     150     .06       0   357.6    .045       0  392.54     .06       0
  647.95     .05       0  776.61      .1       0
#XS Ineff= 2 , 0
           351.6    2512  398.54            2512
Permanent Ineff=
       F       F
Bank Sta=357.6,392.54
XS Rating Curve= 0 ,0
Exp/Cntr=0.5,0.3

Type RM Length L Ch R = 1 ,17403   ,170.1,174.7,171.4
XS GIS Cut Line= 2
2282676.15487873485777.8006226852283384.21482601485896.032021011
#Sta/Elev= 30
       0 2541.64    52.7 2533.92   114.2 2526.69     146 2524.05   162.2 2523.34
   170.3 2521.32   178.5  2521.3   182.5 2520.59   190.6 2515.59   194.7 2513.62
   198.7 2512.79     219 2512.22   235.8 2512.76   255.5  2512.4     288 2512.78
   316.3 2511.86   336.7 2512.28   341.6 2512.07     347 2510.95   352.8 2509.53
   356.9 2509.65   364.4 2510.97   373.1 2512.91   377.2 2513.46   446.1 2513.54
   470.4 2513.28   482.6 2513.69   616.4 2515.51   673.2 2515.49   717.9    2516
#Mann= 7 ,-1,0
       0     .08       0      50      .1       0     150     .06       0
     250      .1       0     347    .045       0   364.4      .1       0
     450     .05       0
#XS Ineff= 2 , 0
                          459.49         2515.12
Permanent Ineff=
       F       F
Bank Sta=347,364.4
XS Rating Curve= 0 ,0
Exp/Cntr(USF)=0,0
Exp/Cntr=0.3,0.1

Type RM Length L Ch R = 1 ,17228   ,183,175.8,160.4
XS GIS Cut Line= 4
2282694.94414642 485920.784872652282855.00492891485924.528984521
2283016.00173937486002.2193058472283345.48358403486064.933179689
#Sta/Elev= 30
       0 2540.42     5.2 2539.55    17.2 2536.47    53.2  2531.2   105.3 2527.52
   129.3  2525.4   145.3  2525.1   170.3 2521.93   174.7 2520.64   183.6 2514.28
   188.1 2511.91   192.5 2510.78   200.4 2510.09   203.4 2509.32   206.4 2508.59
   214.7 2508.36     226  2509.1   236.9 2508.63   241.3 2509.34   245.8 2511.33
   254.7 2512.45   332.2 2511.93   359.4 2511.19   372.3 2511.77   387.9 2511.39
   420.5 2511.44   453.1 2512.83   607.8 2516.41   637.1 2517.65   674.3 2518.14
#Mann= 5 ,-1,0
       0     .06       0      40      .1       0     130     .06       0
   203.4    .045       0   241.3     .05       0
Bank Sta=203.4,241.3
XS Rating Curve= 0 ,0
Exp/Cntr(USF)=0,0
Exp/Cntr=0.3,0.1

Type RM Length L Ch R = 1 ,17052   ,246.3,238.1,230.3
XS GIS Cut Line= 3
2282746.18034124486109.5715313882282910.10961529486119.236783098
2283342.80086016 486104.86634306
#Sta/Elev= 30
       0 2539.89      14 2539.43      26 2535.95    45.1 2532.63    66.1 2529.23
    74.1 2528.76    82.1 2527.33   106.2 2524.25   110.2 2523.03   118.2 2518.19
   126.2  2511.1  129.182509.046   130.2 2508.31   134.2 2507.38   138.2 2507.32
   150.3  2507.5   152.9 2508.94   158.3 2511.35   178.3 2509.63   190.3 2509.42
   198.3 2510.16   202.3 2511.02   222.2  2511.5   278.3  2510.2   326.4  2510.7
   354.4 2510.32   386.4 2511.95   414.4 2512.36   438.4  2513.9   597.1 2517.96
#Mann= 5 ,-1,0
       0     .06       0      80      .1       0  129.18    .045       0
   152.9      .1       0  184.21     .05       0
#XS Ineff= 2 , 0
                           378.8         2514.33
Permanent Ineff=
       F       F
Bank Sta=129.18,152.9
XS Rating Curve= 0 ,0
Exp/Cntr=0.3,0.1

Type RM Length L Ch R = 1 ,16814   ,216.9,215.5,213.4
XS GIS Cut Line= 2
2282835.34834159486382.2466607692283331.44316452 486149.17569679
#Sta/Elev= 30
       0 2531.75     9.8 2531.56    14.2 2530.53      23 2525.51    27.4 2523.85
    40.7 2520.14    45.1 2517.88    57.8 2509.17    61.6 2507.01    62.8 2506.36
    67.2 2505.72    71.6 2506.92    76.6 2508.59    80.5 2509.04    89.3 2509.28
    99.5 2509.31   120.2  2508.8   132.9 2508.82     160 2509.29   173.3 2508.87
   195.4 2509.06   209.5 2508.71   217.5 2508.73   248.4 2509.57   278.1 2510.07
   341.3 2511.75   416.3 2514.16     434  2514.4   479.5  2515.6   548.1 2516.95
#Mann= 6 ,-1,0
       0     .07       0    61.6    .045       0    71.6     .07       0
     100     .05       0     120      .1       0     210     .05       0
Bank Sta=61.6,71.6
XS Rating Curve= 0 ,0
Exp/Cntr(USF)=0,0
Exp/Cntr=0.3,0.1

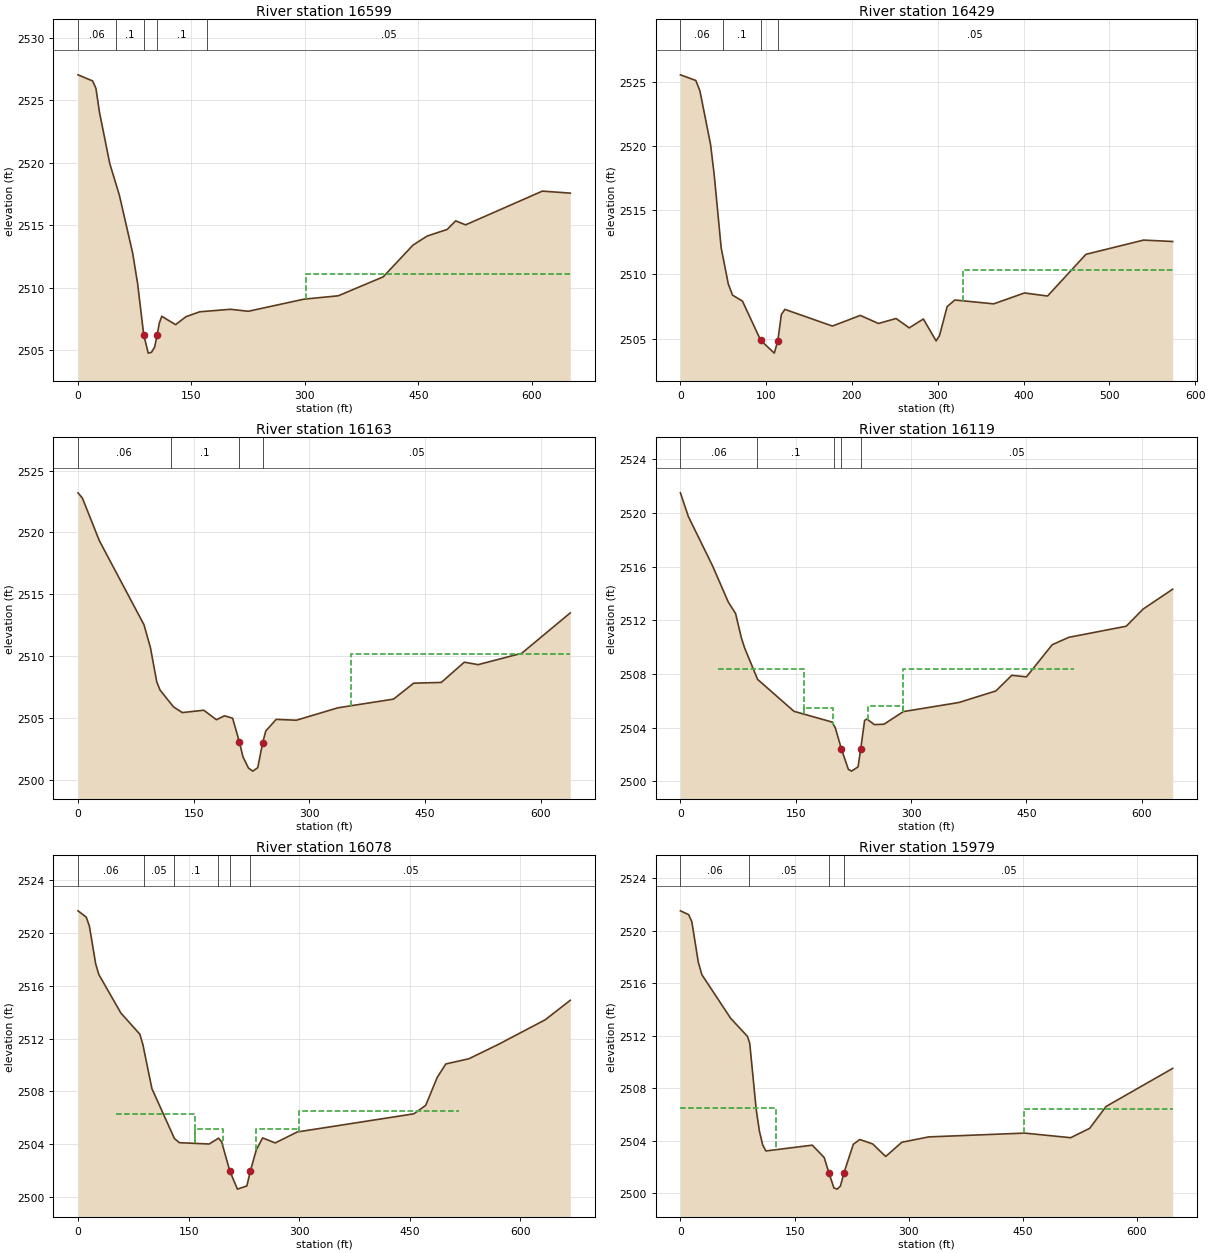
Type RM Length L Ch R = 1 ,16599   ,164.1,169.4,174.1
XS GIS Cut Line= 3
2282879.43470482486602.6454132832283260.68264205486390.577462378
     2283374.682486208.798664993
#Sta/Elev= 30
       0 2527.05    19.3 2526.56    23.7 2525.96    28.3 2524.07      42 2519.94
    54.6 2517.43    72.2 2512.79    78.7 2510.37    86.9 2506.23    92.8 2504.77
      97 2504.83   101.3 2505.25   104.6 2506.23   107.5 2507.17   110.7 2507.72
     129 2507.05   142.8 2507.69     161 2508.08   201.6 2508.28   225.1 2508.12
   298.7 2509.09   344.1 2509.36   403.6 2510.88   442.7 2513.41   461.5 2514.14
     488 2514.67   499.3 2515.36   512.4 2515.04   613.9 2517.74   650.8 2517.58
#Mann= 5 ,-1,0
       0     .06       0      50      .1       0    86.9    .045       0
   104.6      .1       0     170     .05       0
#XS Ineff= 2 , 0
                          301.69         2511.08
Permanent Ineff=
       F       F
Bank Sta=86.9,104.6
XS Rating Curve= 0 ,0
Exp/Cntr=0.3,0.1

Type RM Length L Ch R = 1 ,16429   ,276.6,266.7,253.9
XS GIS Cut Line= 3
2282926.14305446 486737.001260562283076.84355728 486698.62411388
2283450.46985384486510.441605237
#Sta/Elev= 30
       0 2525.55   17.97 2525.11   22.74 2524.29   35.12 2520.13   39.25 2517.84
    47.5 2512.07   55.76 2509.26   60.74 2508.38   72.27 2507.92    93.62504.855
  109.42 2503.86   113.5 2504.81  117.67 2506.87   121.8 2507.27  177.16 2505.97
   209.7  2506.8   230.9 2506.17   251.4 2506.56  266.73 2505.83  283.21 2506.52
  298.08 2504.81  302.04 2505.23  310.97 2507.49  319.91    2508  365.26  2507.7
  401.09 2508.55  427.96 2508.31  472.75 2511.56  539.93 2512.67  573.85 2512.56
#Mann= 4 ,-1,0
       0     .06       0      50      .1       0    93.6    .045       0
   113.5     .05       0
#XS Ineff= 2 , 0
                          329.68         2510.32
Permanent Ineff=
       F       F
Bank Sta=93.6,113.5
XS Rating Curve= 0 ,0
Exp/Cntr(USF)=0,0
Exp/Cntr=0.3,0.1

Type RM Length L Ch R = 1 ,16163   ,31.1,43.7,57.5
BEGIN DESCRIPTION:
structure xs 4
END DESCRIPTION:
XS GIS Cut Line= 5
2283009.34695212486893.2647928722283193.21793783486845.367015252
2283232.93470326486795.8635204622283414.66304169486718.424678178
2283495.30349238486549.226883978
#Sta/Elev= 30
       0 2523.21     5.7 2522.78    27.7 2519.33    85.6 2512.52    93.9 2510.68
   102.1 2507.91   106.3 2507.25   123.7 2505.89   135.2 2505.42   163.1 2505.61
   179.5 2504.84     190 2505.16   200.5 2504.96   209.3 2503.04   213.9 2501.84
     221 2500.93   226.7 2500.68   233.1 2500.96   239.5 2502.99   243.5 2503.93
     257 2504.87   283.1  2504.8   337.3 2505.81   409.2 2506.51   435.3  2507.8
   471.1 2507.86     501  2509.5   518.9  2509.3   575.4 2510.22   638.4 2513.49
#Mann= 4 ,-1,0
       0     .06       0     120      .1       0   209.3    .045       0
   239.5     .05       0
#XS Ineff= 2 , 0
                          353.68         2510.13
Permanent Ineff=
       F       F
Bank Sta=209.3,239.5
XS Rating Curve= 0 ,0
Exp/Cntr(USF)=0,0
Exp/Cntr=0.5,0.3

Type RM Length L Ch R = 1 ,16119   ,41.4,40.9,38.9
BEGIN DESCRIPTION:
strucure xs 3
END DESCRIPTION:
XS GIS Cut Line= 5
2283032.85024279486920.4627422462283318.33877297486825.923917499
2283397.90115023486754.7857919482283460.61502407486683.647666396
2283517.71273011486558.219918712
#Sta/Elev= 30
       0 2521.51    10.4 2519.73    41.4 2516.11    62.2 2513.37    71.7 2512.51
    79.3 2510.68    83.6 2509.92   100.4 2507.59   147.7 2505.21   197.3 2504.41
   201.5 2503.96  209.36  2502.4   218.4 2500.88   222.6 2500.75     231 2501.07
  234.47 2502.41   239.5 2504.53   242.6 2504.64   252.1 2504.22   264.7 2504.25
   289.9 2505.19   362.1 2505.87   410.2 2506.73   430.9  2507.9   449.9 2507.78
   483.5 2510.18     505 2510.73   579.7 2511.56   601.7 2512.84   640.1 2514.32
#Mann= 5 ,-1,0
       0     .06       0     100      .1       0     200     .05       0
  209.36    .045       0  234.47     .05       0
#XS Ineff= 4 ,-1
    48.9  160.11 2508.35  160.11     199 2505.47     244  289.07  2505.6
  289.07  511.49 2508.39
Permanent Ineff=
       F       F       F       F
Bank Sta=209.36,234.47
XS Rating Curve= 0 ,0
Exp/Cntr(USF)=0,0
Exp/Cntr=0.5,0.3

Type RM Length L Ch R = 1 ,16078   ,85.4,98.8,117
BEGIN DESCRIPTION:
structure xs 2
END DESCRIPTION:
XS GIS Cut Line= 5
2283041.73183782486967.7780497022283328.38354507486860.285021127
2283422.23787739486788.4827987882283491.50394701486710.792477462
2283546.05597264486582.649106244
#Sta/Elev= 30
       0 2521.65    11.2 2521.17    15.4  2520.5      24 2517.63    28.2 2516.84
    58.1 2513.93    83.8 2512.33      88 2511.54   100.2 2508.22   130.8 2504.44
   137.5 2504.13   177.9 2504.03   190.6 2504.47   194.8 2504.19   205.9 2501.99
   216.2 2500.62     229 2500.86   233.8    2502   241.8 2503.58   250.4 2504.49
   267.5 2504.11   297.4 2504.94   455.5 2506.31   471.6 2506.95   487.3 2509.07
   498.9 2510.08   530.2 2510.47     571 2511.58   633.8 2513.42   667.7 2514.89
#Mann= 6 ,-1,0
       0     .06       0      90     .05       0     130      .1       0
     190     .05       0   205.9    .045       0   233.8     .05       0
#XS Ineff= 4 ,-1
   50.87  158.14 2506.31  158.14     196  2505.2     242     300  2505.2
     300  517.01  2506.5
Permanent Ineff=
       F       F       F       F
Bank Sta=205.9,233.8
XS Rating Curve= 0 ,0
Exp/Cntr=0.5,0.3

Type RM Length L Ch R = 1 ,15979   ,134,120,105.4
XS GIS Cut Line= 5
2283041.97988198486982.826305125 2283130.4365745486952.616367611
2283272.92838544487004.3081668342283486.16070974486928.687578445
2283650.22464306486866.440575568
#Sta/Elev= 30
       0 2521.52    10.8 2521.23      15 2520.69    23.5  2517.6    28.2 2516.65
      66 2513.33    88.1 2511.95    91.1 2511.41    99.6 2506.36   103.8 2504.73
   108.1 2503.68   112.3 2503.22   173.3 2503.66   188.9 2502.72   195.2 2501.53
   201.7  2500.4     206 2500.31   210.2 2500.54   214.92501.561   227.2 2503.73
   235.7 2504.09   252.7 2503.75   269.7  2502.8   290.9 2503.88   326.2 2504.29
   452.2 2504.58   512.8 2504.23   537.7 2504.94   559.3 2506.61   646.8 2509.51
#Mann= 4 ,-1,0
       0     .06       0      90     .05       0   195.2    .045       0
   214.9     .05       0
#XS Ineff= 2 , 0
          125.41  2506.5  451.94         2506.38
Permanent Ineff=
       F       F
Bank Sta=195.2,214.9
XS Rating Curve= 0 ,0
Exp/Cntr(USF)=0,0
Exp/Cntr=0.3,0.1