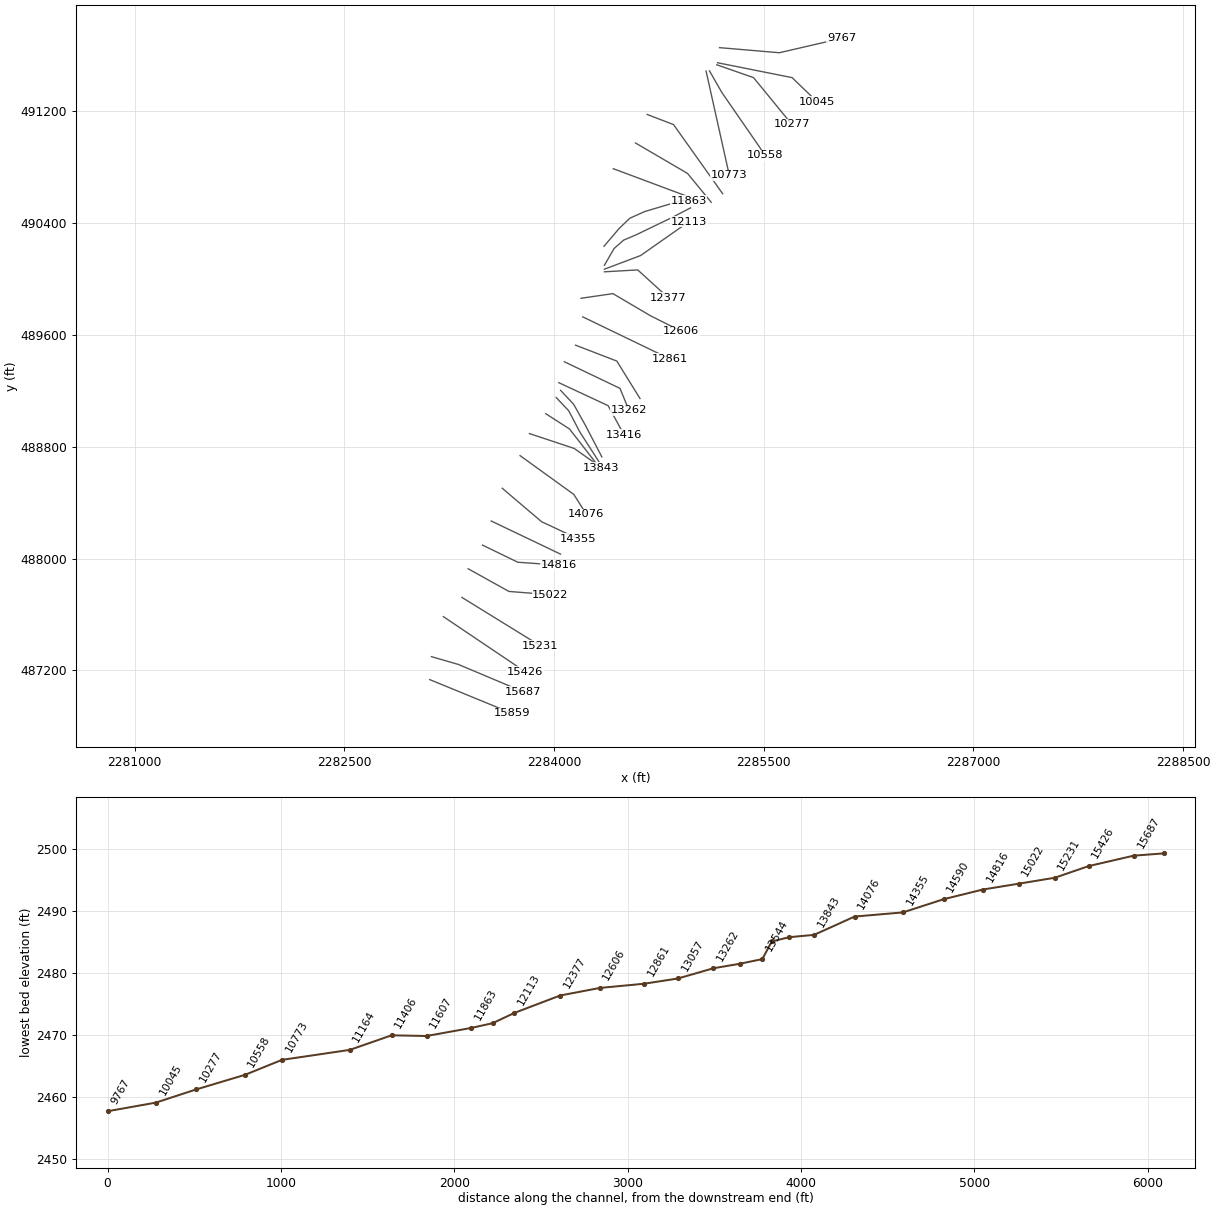
HEC-RAS study THOMASCK.prj: THOMASCK

--- THOMASCK.g01 (geometry) --- (continued)

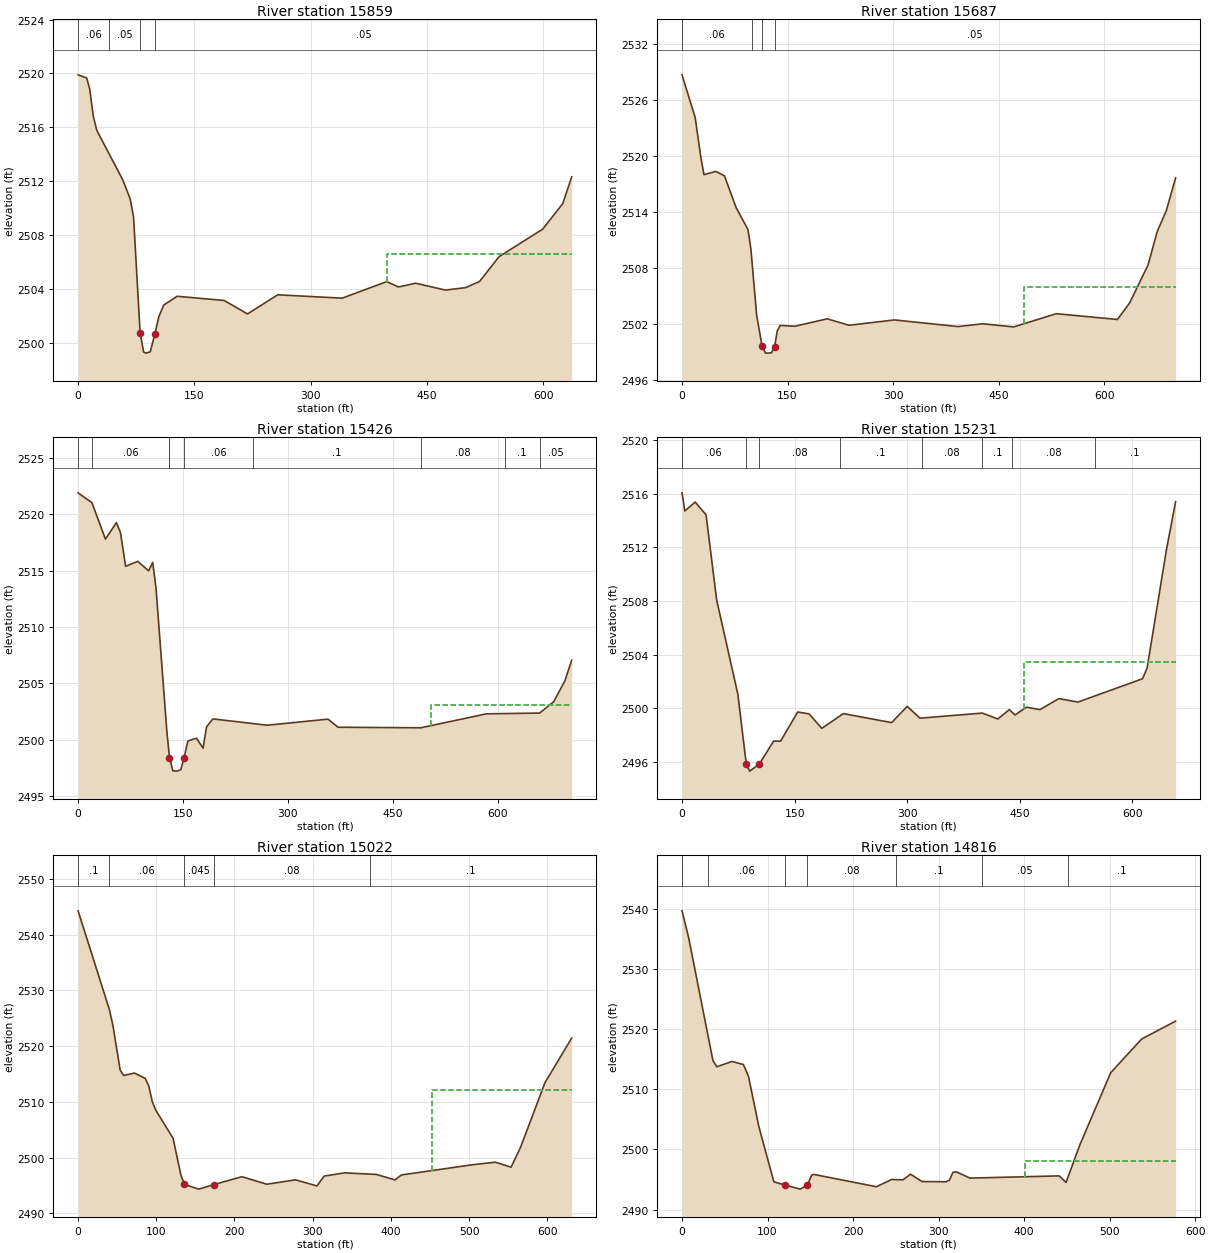
Type RM Length L Ch R = 1 ,15859   ,169.9,172.2,173.9
BEGIN DESCRIPTION:
IFA placed to uncross upstream profiles between structure xs 4 - structure xs 2
END DESCRIPTION:
XS GIS Cut Line= 2
 2283110.0154518 487134.495654192283698.87451203486892.777078901
#Sta/Elev= 30
       0  2519.9      11 2519.67    14.9 2518.87    19.6 2516.82    24.1 2515.78
    57.8 2512.08    67.2 2510.68    71.5 2509.36   79.992500.742    84.5 2499.32
    87.7 2499.24    93.1 2499.34   99.132500.692   104.2 2501.96   110.4 2502.81
   127.7 2503.46   188.3 2503.15   218.5 2502.15   257.4 2503.57   340.5 2503.32
   398.1 2504.55   413.1 2504.15   435.3 2504.43   473.6 2503.92   499.6  2504.1
   517.7 2504.56   542.8  2506.4     599 2508.44     625 2510.34   636.5 2512.33
#Mann= 4 ,-1,0
       0     .06       0      40     .05       0   79.99    .045       0
   99.13     .05       0
#XS Ineff= 2 , 0
                          398.31         2506.62
Permanent Ineff=
       F       F
Bank Sta=79.99,99.13
XS Rating Curve= 0 ,0
Exp/Cntr(USF)=0,0
Exp/Cntr=0.3,0.1

Type RM Length L Ch R = 1 ,15687   ,267.2,261.3,255
XS GIS Cut Line= 3
2283122.20673216487298.6860080542283314.64280237487242.970115585
2283776.38342388487048.552592895
#Sta/Elev= 30
       0 2528.73    18.7 2524.16      27 2519.78    31.2 2518.02    47.9 2518.37
    60.3  2517.9      77 2514.47    93.7 2512.14    97.8 2510.12   106.1 2502.95
113.71342499.633   118.6 2498.88     127 2498.91  131.61 2499.57   135.3 2501.25
   139.5 2501.85   160.3 2501.76   206.3 2502.56   237.3 2501.87   301.8 2502.44
   392.2 2501.73   427.7 2502.03   471.1 2501.69   531.9 2503.11   618.7 2502.49
     636 2504.26   662.1 2508.32   675.1  2511.9   688.1 2514.16   701.3 2517.67
#Mann= 4 ,-1,0
       0     .06       0     100     .05       0113.7134    .045       0
  131.61     .05       0
#XS Ineff= 2 , 0
                          486.31         2505.99
Permanent Ineff=
       F       F
Bank Sta=113.7134,131.61
XS Rating Curve= 0 ,0
Exp/Cntr=0.3,0.1

Type RM Length L Ch R = 1 ,15426   ,193.7,195,195.3
XS GIS Cut Line= 2
2283207.77837288487584.8291098032283793.31586829487190.657332257
#Sta/Elev= 30
       0 2521.92    19.8 2521.04    39.1 2517.81    54.8 2519.27    60.6 2518.39
      68 2515.39    85.3 2515.83   100.9 2514.99   106.7 2515.74   111.4 2513.48
   126.8 2500.82   130.7 2498.39   135.5 2497.22   141.2 2497.19     147 2497.32
   151.42498.357     157 2499.87   169.2 2500.12   178.7 2499.24   183.7 2501.13
   192.8 2501.83   270.5 2501.27   357.5 2501.81   371.8 2501.09     490 2501.04
   583.9 2502.28     660 2502.35   680.2 2503.36   696.2 2505.22   705.9 2507.05
#Mann= 9 ,-1,0
       0      .1       0      20     .06       0     130     .07       0
   130.7    .045       0   151.4     .06       0     250      .1       0
     490     .08       0     610      .1       0     660     .05       0
#XS Ineff= 2 , 0
                          505.24          2503.1
Permanent Ineff=
       F       F
Bank Sta=130.7,151.4
XS Rating Curve= 0 ,0
Exp/Cntr(USF)=0,0
Exp/Cntr=0.3,0.1

Type RM Length L Ch R = 1 ,15231   ,207.5,208.8,208.3
XS GIS Cut Line= 2
2283340.90235052487722.1132117452283900.43906905487376.822894739
#Sta/Elev= 30
       0 2516.07     3.8 2514.72    17.6 2515.38    32.1 2514.42    46.1  2508.1
    74.4 2501.05    85.6 2495.84    90.3 2495.31  103.122495.846   122.2 2497.56
   131.3 2497.54   154.1 2499.72   169.3 2499.58   186.2  2498.5     215  2499.6
   279.2 2498.93     300 2500.14     317 2499.26     400 2499.64   420.7  2499.2
   436.1  2499.9   443.6  2499.5   458.8 2500.08   476.8  2499.9   502.1 2500.72
   527.3 2500.46   613.5  2502.2   619.6 2503.01   645.4 2511.86   657.5  2515.4
#Mann= 8 ,-1,0
       0     .06       0    85.6    .045       0  103.12     .08       0
     210      .1       0     320     .08       0     400      .1       0
     440     .08       0     550      .1       0
#XS Ineff= 2 , 0
                          455.91         2503.46
Permanent Ineff=
       F       F
Bank Sta=85.6,103.12
XS Rating Curve= 0 ,0
Exp/Cntr(USF)=0,0
Exp/Cntr=0.3,0.1

Type RM Length L Ch R = 1 ,15022   ,204.6,206.1,207.8
XS GIS Cut Line= 3
2283385.21891862487927.3461721462283676.70865571487765.172725912
2283973.42505097487741.768666888
#Sta/Elev= 30
       0 2544.29      40 2526.58    44.6 2523.67    53.8 2515.72    58.3 2514.74
      72 2515.18    85.8 2514.23    90.4 2512.86    94.9 2510.03    99.5 2508.47
   121.4 2503.49   131.5 2496.85135.98662495.197   154.4 2494.35  173.842495.178
   209.4 2496.58   241.4 2495.23     278 2496.02   305.5 2494.92   314.6 2496.69
   341.1 2497.27   381.4 2496.99   405.3    2496   413.3 2496.89   505.6 2498.75
   533.7 2499.18   553.7 2498.29   565.8 2501.85   597.1 2513.47   631.2 2521.46
#Mann= 5 ,-1,0
       0      .1       0      40     .06       0135.9866    .045       0
  173.84     .08       0  373.57      .1       0
#XS Ineff= 2 , 0
                          452.69         2512.17
Permanent Ineff=
       F       F
Bank Sta=135.9866,173.84
XS Rating Curve= 0 ,0
Exp/Cntr=0.3,0.1

Type RM Length L Ch R = 1 ,14816   ,205.6,226,223.8
XS GIS Cut Line= 3
2283487.54673214488096.5243988592283740.45695765487974.100132618
2284035.91882728487952.889418872
#Sta/Elev= 30
       0 2539.62     7.7 2535.22    36.2 2514.75    40.7 2513.73    58.5 2514.61
    71.8  2514.1    77.8 2512.11    89.8 2503.84   107.4 2494.63   120.7 2494.07
   138.5 2493.41   146.7 2494.13   151.8 2495.77   154.6 2495.84   227.3 2493.81
   245.1 2495.01   258.4 2494.95   267.3 2495.89   280.7 2494.67   308.8 2494.63
   312.8  2494.9   316.8 2496.19   320.8 2496.28   336.8 2495.24   441.1 2495.61
   449.1 2494.52   465.2 2500.74   501.3 2512.73   537.4 2518.32   577.2 2521.31
#Mann= 7 ,-1,0
       0      .1       0      30     .06       0   120.7    .045       0
   146.7     .08       0     250      .1       0  350.98     .05       0
  450.98      .1       0
#XS Ineff= 2 , 0
                          400.51         2498.01
Permanent Ineff=
       F       F
Bank Sta=120.7,146.7
XS Rating Curve= 0 ,0
Exp/Cntr(USF)=0,0
Exp/Cntr=0.3,0.1

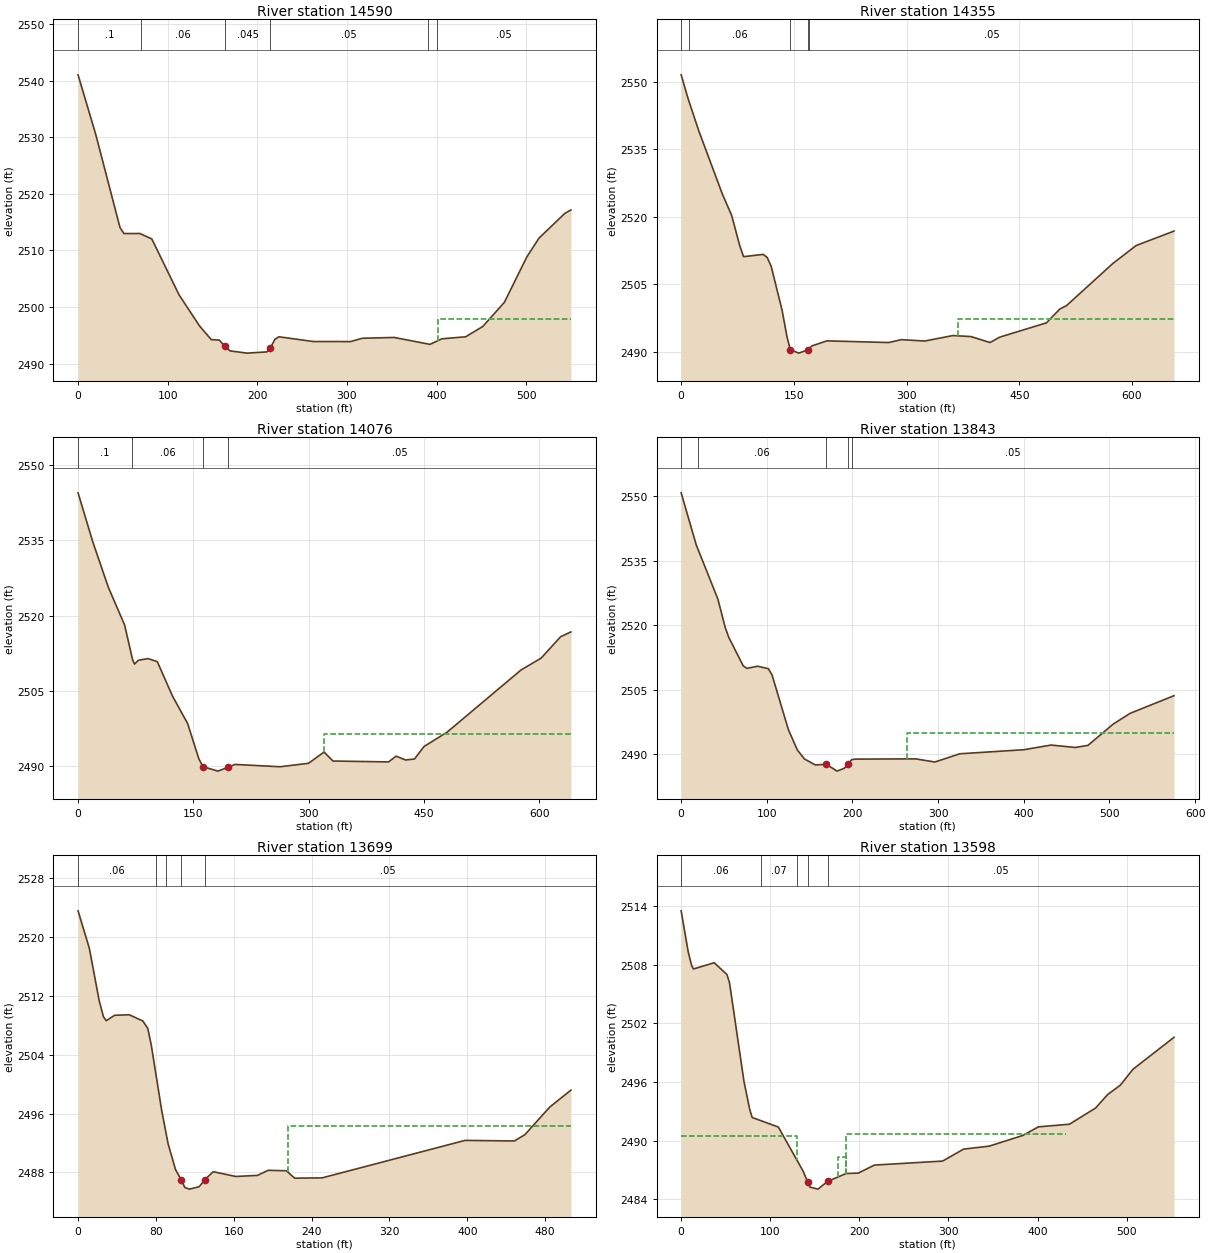
Type RM Length L Ch R = 1 ,14590   ,237.9,235.1,231.9
XS GIS Cut Line= 2
2283549.94859666488269.1695573622284046.04341959 488032.04247219
#Sta/Elev= 30
       0 2541.06    19.7 2530.54    46.8 2514.05    51.2 2512.99      69    2513
    82.3 2512.04   112.6 2502.18   135.5 2496.66   148.6 2494.24   157.6 2494.16
   163.6 2493.05   169.6 2492.24   188.7 2491.85   210.8 2492.07   214.6 2492.79
   219.7 2494.31   224.1 2494.74   262.6  2493.9   303.9 2493.89   317.2 2494.48
   352.7 2494.62   392.6  2493.4   405.9 2494.38   432.5 2494.74   451.6 2496.57
   475.6 2500.82   500.8 2508.89   514.3 2512.19   543.3 2516.59   549.9 2517.16
#Mann= 6 ,-1,0
       0      .1       0      70     .06       0   163.6    .045       0
   214.6     .05       0     390      .1       0     400     .05       0
#XS Ineff= 2 , 0
                          401.24         2497.91
Permanent Ineff=
       F       F
Bank Sta=163.6,214.6
XS Rating Curve= 0 ,0
Exp/Cntr(USF)=0,0
Exp/Cntr=0.3,0.1

Type RM Length L Ch R = 1 ,14355   ,277.4,279,280.2
XS GIS Cut Line= 3
2283628.88024926488503.1695736622283910.36565571488264.116740218
2284169.76003108488142.289881289
#Sta/Elev= 30
       0 2551.51     9.4 2546.13    23.6 2539.01    54.8 2525.06    67.3 2520.26
    77.8 2513.67      83 2511.14   109.3 2511.64   114.5 2510.95   119.8    2509
   134.3 2499.26   140.8 2493.38   145.2  2490.5   156.5 2489.72   168.3 2490.44
     174 2491.32   193.9 2492.44   276.2 2492.07     293 2492.71   324.4 2492.41
   361.5 2493.62   385.6  2493.4   411.1 2492.07     424 2493.27   486.2 2496.45
   503.9 2499.51   512.7 2500.25   574.3  2509.6   605.5 2513.61   655.9 2516.82
#Mann= 5 ,-1,0
       0      .1       0      10     .06       0   145.2    .045       0
   168.3     .06       0     170     .05       0
#XS Ineff= 2 , 0
                          368.34         2497.19
Permanent Ineff=
       F       F
Bank Sta=145.2,168.3
XS Rating Curve= 0 ,0
Exp/Cntr=0.3,0.1

Type RM Length L Ch R = 1 ,14076   ,224.3,232.8,239.5
XS GIS Cut Line= 3
2283756.56989872488736.6195873052284140.68624744488459.495244145
2284230.37375699488317.882663761
#Sta/Elev= 30
       0  2544.4    19.2 2534.63    39.4 2525.61    60.6  2518.1    70.9 2511.24
    73.5 2510.33    78.4 2511.09      91 2511.43   103.1 2510.82   122.8    2504
   142.6  2498.5   157.3 2491.44   162.6 2489.93     182 2489.05   195.5 2489.83
   204.1 2490.38   262.9 2489.92   299.9 2490.61   320.1 2492.84   331.7 2491.06
     404 2490.88   413.8 2492.03   426.2 2491.26   437.7 2491.46   450.3 2493.96
   480.2  2496.8   576.4 2509.17   602.5 2511.52   627.9 2515.78   641.3 2516.74
#Mann= 4 ,-1,0
       0      .1       0      70     .06       0   162.6    .045       0
   195.5     .05       0
#XS Ineff= 2 , 0
                          319.44         2496.44
Permanent Ineff=
       F       F
Bank Sta=162.6,195.5
XS Rating Curve= 0 ,0
Exp/Cntr=0.3,0.1

Type RM Length L Ch R = 1 ,13843   ,149.4,144,138.4
XS GIS Cut Line= 3
2283823.42934929488894.539573727  2284143.795961 488788.13963689
2284338.07038311488650.929457827
#Sta/Elev= 30
       0  2550.8    17.6 2538.71    42.9 2526.09    51.4 2519.52    55.6  2517.2
    72.4 2510.59    76.7 2509.99    89.3 2510.49   101.9  2509.9   106.2 2508.41
   125.2 2495.74   135.7    2491     144 2488.91   156.7 2487.53   169.4 2487.69
     182  2486.1   190.5 2486.77   194.7 2487.66   198.9 2488.75   203.1 2488.89
   273.8 2488.95   296.2 2488.22   325.3 2490.13   400.2 2491.08   431.8 2492.16
   460.2  2491.6   474.9 2492.09   504.5 2497.05   524.1 2499.53   575.4 2503.64
#Mann= 5 ,-1,0
       0      .1       0      20     .06       0   169.4    .045       0
   194.7     .06       0     200     .05       0
#XS Ineff= 2 , 0
                          263.32         2495.08
Permanent Ineff=
       F       F
Bank Sta=169.4,194.7
XS Rating Curve= 0 ,0
Exp/Cntr(USF)=0,0
Exp/Cntr=0.3,0.1

Type RM Length L Ch R = 1 ,13699   ,112,101,89.8
BEGIN DESCRIPTION:
structure xs 4
END DESCRIPTION:
XS GIS Cut Line= 3
2283939.89389717 489036.902712212284110.01926781488927.507460646
2284296.69090874 488687.26204964
#Sta/Elev= 30
       0 2523.58    11.6 2518.48    21.7 2511.36    26.1 2509.17    28.9 2508.63
    37.6 2509.37    52.6 2509.44    66.6 2508.59    71.7 2507.57    75.3 2505.27
    85.9 2496.46    92.6 2491.85   100.2 2488.37  105.96 2486.98   109.7 2485.95
   114.5 2485.72   124.5 2486.05   130.3 2487.01   138.9 2488.09   162.1 2487.44
   184.4 2487.59   195.3 2488.28     214 2488.22   222.6 2487.21   250.8 2487.25
   397.7 2492.35   448.4 2492.27   459.2 2493.13   484.8 2496.89   506.5 2499.19
#Mann= 5 ,-1,0
       0     .06       0      80     .07       0      90     .05       0
  105.96    .045       0   130.3     .05       0
#XS Ineff= 2 , 0
                          215.32         2494.32
Permanent Ineff=
       F       F
Bank Sta=105.96,130.3
XS Rating Curve= 0 ,0
Exp/Cntr(USF)=0,0
Exp/Cntr=0.5,0.3

Type RM Length L Ch R = 1 ,13598   ,55.4,54.1,55.3
BEGIN DESCRIPTION:
structure xs 3
END DESCRIPTION:
XS GIS Cut Line= 5
2284014.66676883489152.3985928952284103.95891236489058.114155377
2284129.24590562489010.7117140642284183.32752153488906.708606532
 2284319.8275873 488694.46500559
#Sta/Elev= 30
       0  2513.5       8 2509.26    11.8  2507.9    13.8 2507.55    37.1 2508.19
    51.4 2506.98    54.3 2506.13    70.5 2496.05    76.9 2493.21    79.7 2492.36
   109.1 2491.38   136.6 2486.92  141.89 2485.79   144.5 2485.24   153.6 2485.03
   164.3 2485.82   185.3 2486.63   198.8 2486.67   216.9 2487.49   293.5  2487.9
   316.9 2489.12   345.9 2489.43   383.5 2490.52   400.9  2491.4   435.8 2491.67
   465.1 2493.32   478.6  2494.7   492.9 2495.66   507.1 2497.29   553.2 2500.56
#Mann= 5 ,-1,0
       0     .06       0      90     .07       0  129.86     .05       0
  141.89    .045       0   164.3     .05       0
#XS Ineff= 3 ,-1
       0   129.9 2490.49     176     185 2488.33     185     432 2490.65
Permanent Ineff=
       F       F       F
Bank Sta=141.89,164.3
XS Rating Curve= 0 ,0
Exp/Cntr=0.5,0.3

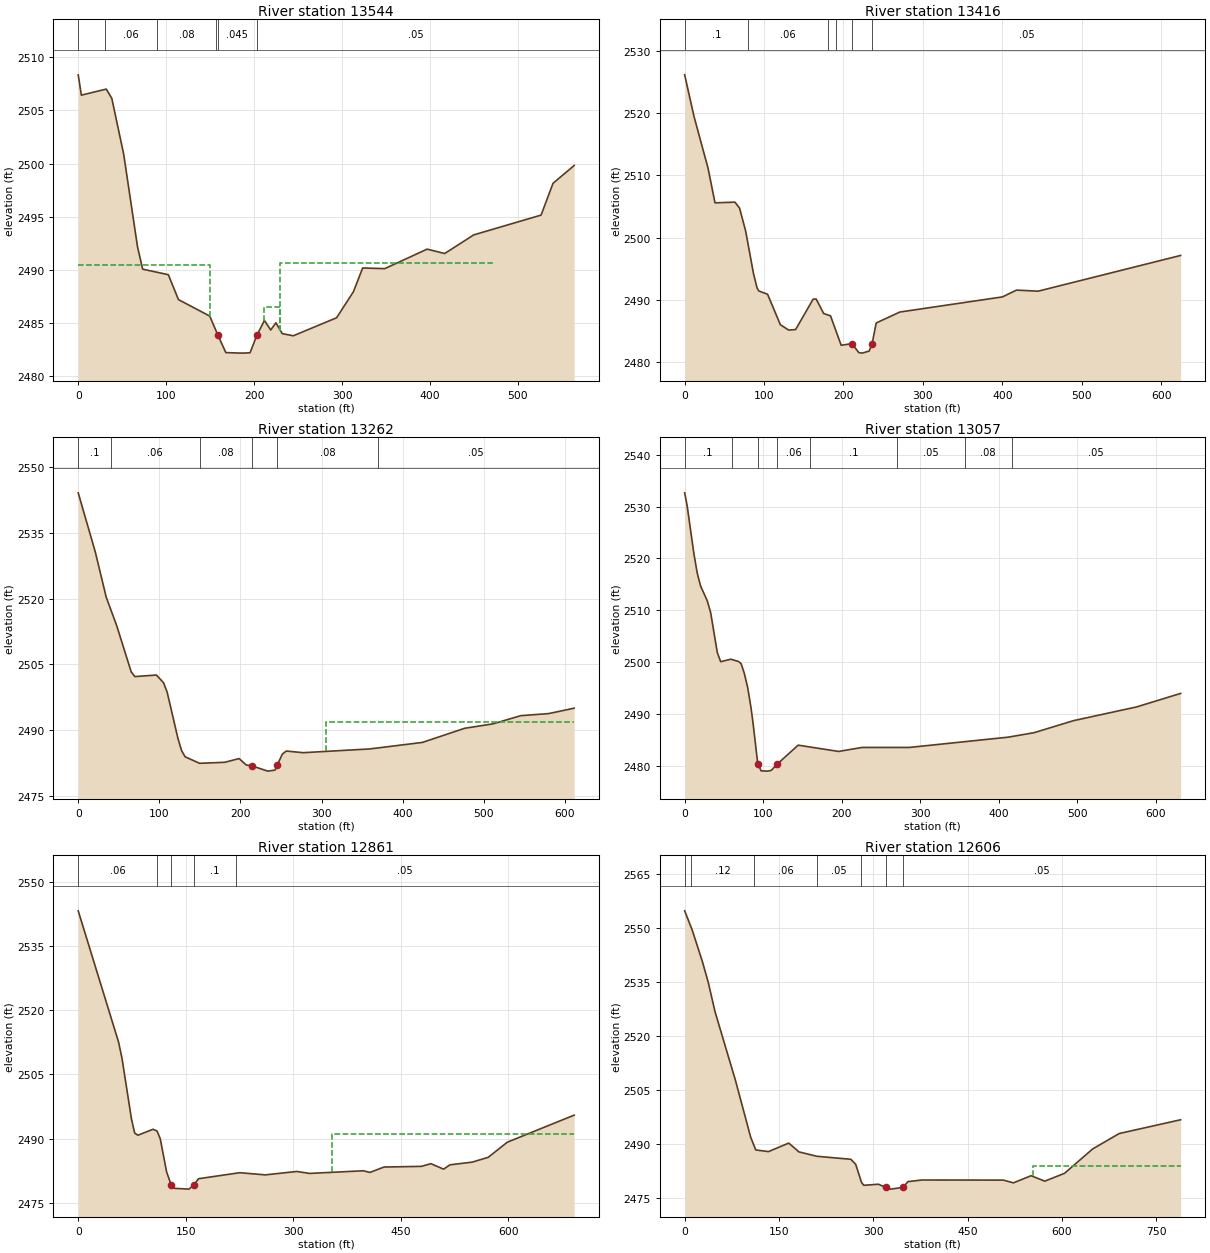
Type RM Length L Ch R = 1 ,13544   ,109.7,128.4,146.2
BEGIN DESCRIPTION:
structure xs 2
END DESCRIPTION:
XS GIS Cut Line= 4
2284046.04341959489204.1574940732284139.64621637489104.314510842
2284223.88873347488953.5100049212284341.41224498488727.823261577
#Sta/Elev= 30
       0 2508.34     3.6 2506.43    31.9    2507    38.2 2506.13    51.7 2500.89
    67.4  2492.2    73.3 2490.08   102.5 2489.56     114 2487.22   149.6 2485.67
   158.8 2483.89   167.9 2482.24   186.3 2482.19   195.4 2482.22  203.22 2483.88
   211.8 2485.26   218.9 2484.36   224.8 2485.04   232.1 2484.02   244.6 2483.82
   293.8 2485.51     313 2487.96   323.5 2490.19   348.6 2490.13   396.8 2491.96
   416.8 2491.55   449.8  2493.3   526.4 2495.16     540 2498.15     564 2499.82
#Mann= 6 ,-1,0
       0      .1       0      30     .06       0      90     .08       0
  156.86     .05       0   158.8    .045       0  203.22     .05       0
#XS Ineff= 3 ,-1
       0     150 2490.49   211.5     230  2486.5     230  471.55 2490.67
Permanent Ineff=
       F       F       F
Bank Sta=158.8,203.22
XS Rating Curve= 0 ,0
Exp/Cntr(USF)=0,0
Exp/Cntr=0.5,0.3

Type RM Length L Ch R = 1 ,13416   ,154,153.8,153.2
XS GIS Cut Line= 3
2284033.55328143489258.662772915 2284386.7322102489093.987930905
2284498.98362687488887.651463006
#Sta/Elev= 30
       0 2526.14    11.7 2519.48    29.4 2511.16    38.2 2505.58    63.3 2505.69
    69.1 2504.74    76.8 2501.05    86.7  2494.2    91.2 2491.89    93.4 2491.42
   104.4  2490.9   120.5 2486.01   130.9 2485.15   139.7 2485.22   161.8 2490.11
   165.6 2490.13     175 2487.81   183.7 2487.42   197.1  2482.7   210.8 2482.97
   219.2 2481.53   223.6 2481.44   232.4 2481.78  236.09 2482.97   241.2 2486.28
     271 2488.04   400.2 2490.47   417.9 2491.56   445.2 2491.39   624.6 2497.13
#Mann= 6 ,-1,0
       0      .1       0      80     .06       0     180     .08       0
     190     .05       0   210.8    .045       0  236.09     .05       0
Bank Sta=210.8,236.09
XS Rating Curve= 0 ,0
Exp/Cntr(USF)=0,0
Exp/Cntr=0.3,0.1

Type RM Length L Ch R = 1 ,13262   ,197.5,204.2,205.8
XS GIS Cut Line= 3
2284073.24776548489408.3165461092284471.29092663489217.862119661
2284535.87408854489060.358286025
#Sta/Elev= 30
       0 2544.07      21 2530.65    34.5 2520.34    47.6 2513.75    65.3 2503.33
    69.8 2502.23    96.4 2502.59   105.2 2500.84   109.7 2498.68     123 2488.14
   127.4 2485.41   131.8 2483.98   149.6 2482.49   180.6 2482.72   198.4 2483.57
   207.2 2482.11   214.62481.888   233.8 2480.71   242.7 2480.95  245.42 2482.07
   251.6 2484.56   256.5 2485.28   277.5 2484.91   359.4 2485.76   424.5 2487.25
   476.6 2490.47   511.2 2491.46   545.8 2493.34   580.1 2493.81   611.5 2495.04
#Mann= 6 ,-1,0
       0      .1       0      40     .06       0     150     .08       0
   214.6    .045       0  245.42     .08       0     370     .05       0
#XS Ineff= 2 , 0
                          305.38         2491.84
Permanent Ineff=
       F       F
Bank Sta=214.6,245.42
XS Rating Curve= 0 ,0
Exp/Cntr(USF)=0,0
Exp/Cntr=0.3,0.1

Type RM Length L Ch R = 1 ,13057   ,198.1,196.3,194.5
XS GIS Cut Line= 3
2284153.32766442489527.0297992422284448.53544574489413.203740212
2284614.39611559489145.274728376
#Sta/Elev= 30
       0 2532.64     3.1 2530.19    11.6 2521.07    15.9 2517.24    20.2 2514.72
    28.8 2511.84    33.1 2509.56    41.6 2501.85    45.9 2500.13    58.8 2500.61
    68.6 2500.17    71.9 2499.74    75.9 2497.91    80.2 2495.18    84.5 2491.24
    87.2 2488.14    93.1 2480.44    97.4 2479.12   105.2 2479.06   110.2 2479.19
   118.1 2480.45   144.5 2484.06     196 2482.85     226 2483.62     286 2483.62
     412  2485.6   444.9 2486.46   495.2 2488.78   575.2 2491.41   631.5 2494.02
#Mann= 8 ,-1,0
       0      .1       0      60     .06       0    93.1    .045       0
   118.1     .06       0     160      .1       0     270     .05       0
  356.39     .08       0  416.39     .05       0
Bank Sta=93.1,118.1
XS Rating Curve= 0 ,0
Exp/Cntr=0.3,0.1

Type RM Length L Ch R = 1 ,12861   ,258,255.3,252.5
XS GIS Cut Line= 2
2284205.16817411489729.3731871092284828.14678823489428.804206342
#Sta/Elev= 30
       0 2543.25    56.3 2512.57    61.1 2508.77    74.3 2494.58    78.8  2491.3
    83.3 2490.81   104.3  2492.2   109.9  2491.8   114.4 2490.01   123.3 2482.23
  129.712479.185   134.2  2478.4   154.3 2478.21   161.2 2479.12   167.7 2480.64
   225.4 2482.05   260.9 2481.54     305 2482.34   322.6 2481.88   397.8  2482.5
   406.8 2482.11   426.5 2483.37   478.7 2483.53   491.9 2484.16   509.6 2482.88
   518.5 2483.89   549.6 2484.52   571.8 2485.64   598.5 2489.18   691.7  2495.5
#Mann= 5 ,-1,0
       0     .06       0     110      .1       0  129.71    .045       0
   161.2      .1       0     220     .05       0
#XS Ineff= 2 , 0
                          353.76         2491.03
Permanent Ineff=
       F       F
Bank Sta=129.71,161.2
XS Rating Curve= 0 ,0
Exp/Cntr(USF)=0,0
Exp/Cntr=0.3,0.1

Type RM Length L Ch R = 1 ,12606   ,233.3,228.8,223.5
XS GIS Cut Line= 4
2284192.39299441489862.465423212 2284420.4546067489895.778159159
 2284689.4969099489737.381804832     2284909.165      489627.017
#Sta/Elev= 30
       0 2554.73    11.9 2549.44    28.1 2540.69    37.5 2534.88    48.3 2526.71
    80.6 2507.79   104.9 2491.95     113  2488.4   133.2 2487.94   165.5  2490.3
   181.7 2487.86     210 2486.65   264.3  2485.8   271.9 2484.42   281.2 2479.39
   284.8 2478.59   308.1 2478.89   319.8 2477.99   327.6 2477.53  347.162478.007
   354.9 2479.61   377.5 2480.06   506.8 2480.03   522.6 2479.27   550.8 2481.25
   572.5 2479.74   603.9 2481.91   648.6 2488.67   690.8 2492.95   788.5 2496.77
#Mann= 7 ,-1,0
       0      .1       0      10     .12       0     110     .06       0
     210     .05       0  280.48      .1       0   319.8    .045       0
  347.16     .05       0
#XS Ineff= 2 , 0
                          553.89         2484.03
Permanent Ineff=
       F       F
Bank Sta=319.8,347.16
XS Rating Curve= 0 ,0
Exp/Cntr=0.3,0.1

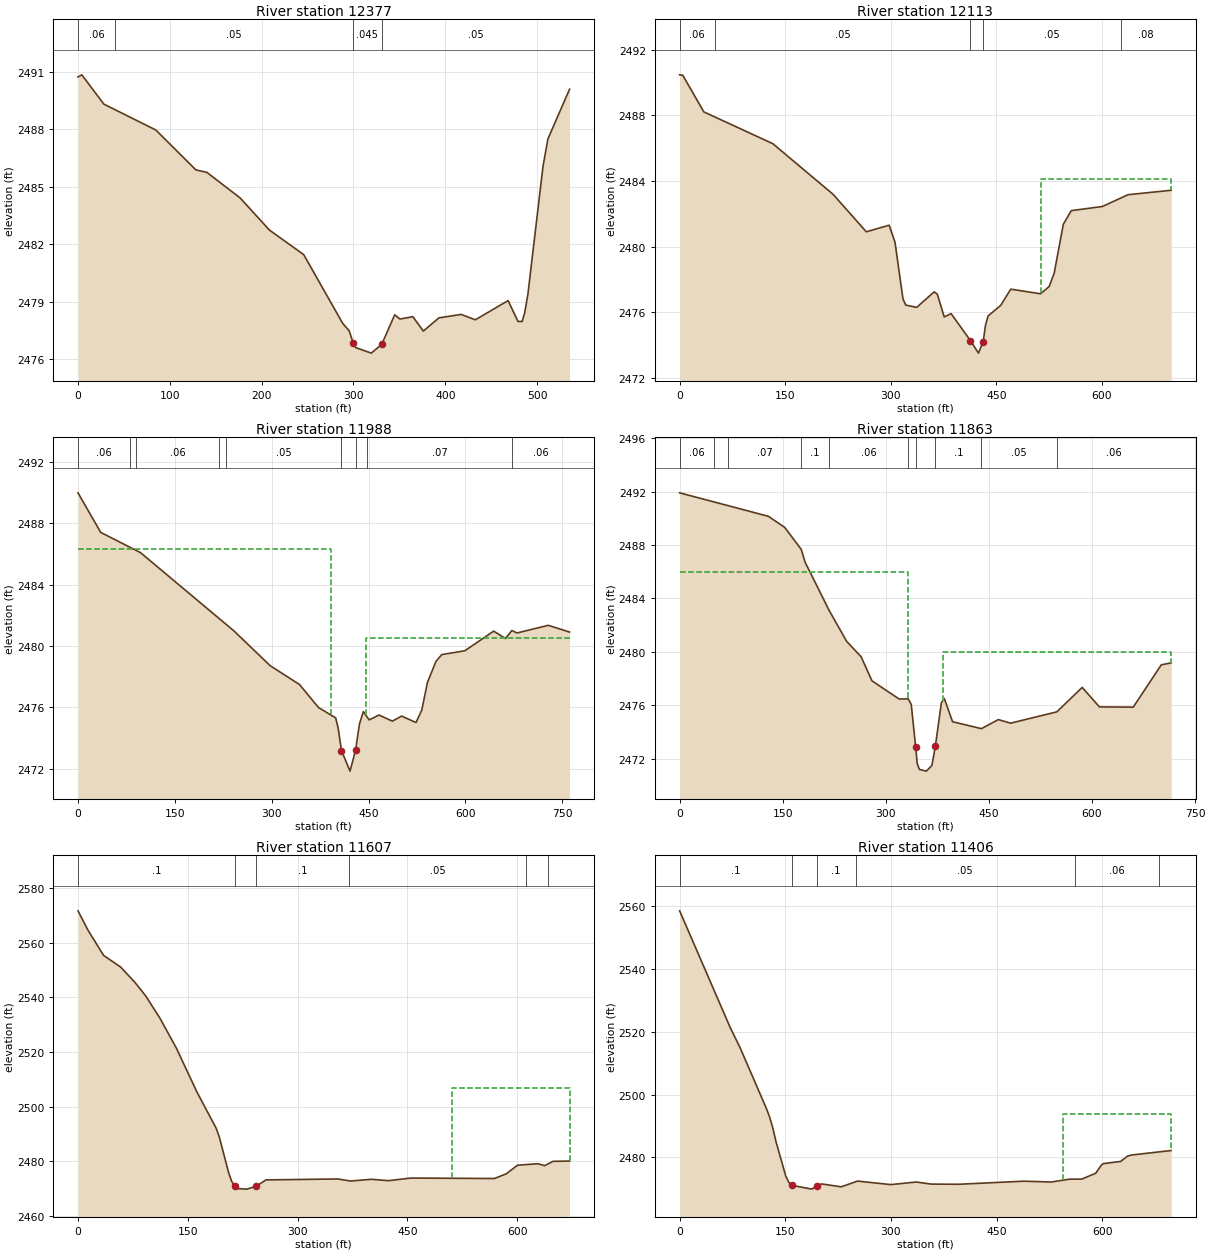
Type RM Length L Ch R = 1 ,12377   ,235.8,263.8,292
XS GIS Cut Line= 3
2284359.99349217490051.8928245442284598.16060842490065.413228523
2284817.60716531489865.727262062
#Sta/Elev= 30
       0 2490.72     4.2 2490.83    28.2  2489.3    84.8 2487.95   128.4 2485.87
   140.4 2485.74   176.5 2484.41   208.5 2482.73   245.8 2481.45   288.3 2477.86
   295.4 2477.47   299.6 2476.85   302.4  2476.6   319.4 2476.31   330.8 2476.77
   344.9 2478.31   350.6 2478.09   364.7 2478.21   376.1 2477.46     393 2478.15
   417.2 2478.33   432.7 2478.05   468.4 2479.05   479.2 2477.96   483.7 2477.96
   486.5 2478.42     490  2479.4   506.3 2486.02   511.7 2487.48   535.3 2490.08
#Mann= 4 ,-1,0
       0     .06       0      40     .05       0   299.6    .045       0
   330.8     .05       0
Bank Sta=299.6,330.8
XS Rating Curve= 0 ,0
Exp/Cntr(USF)=0,0
Exp/Cntr=0.3,0.1

Type RM Length L Ch R = 1 ,12113   ,129.3,125.7,122.2
BEGIN DESCRIPTION:
structure xs 4
END DESCRIPTION:
XS GIS Cut Line= 3
2284359.99349217  490070.61338392284618.96122993490168.376304979
2284964.25154693490410.703545529
#Sta/Elev= 30
       0 2490.47     4.5 2490.44    34.4 2488.21   132.5 2486.27   218.2 2483.18
   265.3  2480.9   297.8  2481.3   306.1 2480.26   317.4 2476.81   321.3 2476.43
   336.9 2476.29   361.8 2477.24   366.3 2477.09     376 2475.71   385.8 2475.91
   413.2 2474.27   424.7  2473.5   431.4 2474.19   434.7  2475.2   438.4 2475.77
   456.3 2476.41   470.6  2477.4   512.9 2477.12   525.2 2477.56   532.4 2478.39
   545.3 2481.36   556.7 2482.19   600.8 2482.44   637.2 2483.16   698.6 2483.43
#Mann= 5 ,-1,0
       0     .06       0      50     .05       0   413.2    .045       0
   431.4     .05       0  626.81     .08       0
#XS Ineff= 2 , 0
                          513.98          2484.1
Permanent Ineff=
       F       F
Bank Sta=413.2,431.4
XS Rating Curve= 0 ,0
Exp/Cntr(USF)=0,0
Exp/Cntr=0.5,0.3

Type RM Length L Ch R = 1 ,11988   ,125.4,124.8,124.3
BEGIN DESCRIPTION:
structure xs 3
END DESCRIPTION:
XS GIS Cut Line= 6
2284359.80850592490098.6707793472284428.77485531490218.187792508
2284497.41690628490278.5095948762284587.89960983490316.990744663
2284843.62782226490440.4654748462284976.39012676 490509.31684775
#Sta/Elev= 30
       0 2489.99    35.2 2487.41    96.8 2486.09   241.1    2481   297.5 2478.72
     343 2477.49   372.4 2475.99   399.1 2475.31   402.9 2474.64     408 2473.18
   421.3 2471.84   429.9 2473.22   435.9 2474.92   441.9 2475.72   450.9 2475.18
   466.1  2475.5   486.8  2475.1   501.2 2475.43   523.4 2475.01   532.3 2475.81
   541.2 2477.63   554.5 2479.01   563.4 2479.44     599 2479.69   643.8 2480.97
   661.9 2480.49   671.9 2481.01   679.9 2480.85   728.3 2481.35   761.2 2480.91
#Mann= 9 ,-1,0
       0     .06       0      80     .05       0      90     .06       0
  217.99     .07       0  229.37     .05       0     408    .045       0
   429.9     .05       0  447.69     .07       0  671.67     .06       0
#XS Ineff= 2 , 0
           392.3  2486.3   445.6         2480.55
Permanent Ineff=
       F       F
Bank Sta=408,429.9
XS Rating Curve= 0 ,0
Exp/Cntr=0.5,0.3

Type RM Length L Ch R = 1 ,11863   ,273.3,256,235.2
BEGIN DESCRIPTION:
structure xs 2
END DESCRIPTION:
XS GIS Cut Line= 6
2284357.01271111490234.8282897132284465.17594294490361.712080902
2284541.28643627490434.9497483862284647.53057156 490482.85172846
2284907.30669427490560.2318501182284962.57820974490561.460106017
#Sta/Elev= 30
       0 2491.91   129.2 2490.15   152.9 2489.32     177 2487.67   182.6 2486.71
   217.9 2483.07   243.1 2480.78     264 2479.64   279.9 2477.83   319.4 2476.47
   332.6 2476.48     337 2476.06  343.472472.864   345.7 2471.64   348.8  2471.2
   358.9 2471.07     367 2471.49   372.1 2472.93   380.8 2476.18   385.1 2476.51
   397.1 2474.77   439.1 2474.25   463.7 2474.93   481.5 2474.66   548.9 2475.51
   585.7 2477.34   610.8 2475.88     660 2475.86   700.8 2479.03   715.2 2479.18
#Mann= 10 ,-1,0
       0     .06       0      50     .05       0      70     .07       0
  176.73      .1       0  216.73     .06       0  332.35     .07       0
  343.47    .045       0   372.1      .1       0   438.9     .05       0
   548.9     .06       0
#XS Ineff= 2 , 0
          332.47    2486  383.04            2480
Permanent Ineff=
       F       F
Bank Sta=343.47,372.1
XS Rating Curve= 0 ,0
Exp/Cntr(USF)=0,0
Exp/Cntr=0.5,0.3

Type RM Length L Ch R = 1 ,11607   ,204.9,201.3,196.4
XS GIS Cut Line= 3
2284423.39666513490789.5407527942284931.41245677490599.761959928
2285051.97965638490552.994187754
#Sta/Elev= 30
       0 2571.74    13.6 2564.68      35  2555.4    58.2 2551.16    77.7 2545.56
    92.5 2540.57   111.9 2532.45   134.6 2521.34   162.5 2505.36   188.7 2492.14
     193 2488.96   205.8 2475.83   210.1 2472.57   214.3 2470.92   218.6 2469.97
   230.9 2469.78   243.4 2470.85     257 2473.16   355.3  2473.5   372.3 2472.75
   401.1 2473.38     424 2472.88   454.8 2473.84   568.9 2473.67   585.1 2475.38
   600.5 2478.54   628.4 2479.09   637.6 2478.38     649 2479.96   671.6 2480.07
#Mann= 6 ,-1,0
       0      .1       0   214.3    .045       0   243.4      .1       0
     370     .05       0  612.31     .06       0  642.31      .1       0
#XS Ineff= 2 , 0
                          510.75         2506.99
Permanent Ineff=
       F       F
Bank Sta=214.3,243.4
XS Rating Curve= 0 ,0
Exp/Cntr=0.3,0.1

Type RM Length L Ch R = 1 ,11406   ,249.6,241.4,231.5
XS GIS Cut Line= 3
2284582.08200384490973.3991742322284954.26844728 490755.85357701
2285123.76180415490549.665782052
#Sta/Elev= 30
       0 2558.49    71.9  2521.3    85.8 2514.94   122.9 2495.73   127.5 2493.03
   132.2 2489.46   136.8 2485.04   150.8 2473.97   155.3 2471.97     160 2471.07
   187.8 2469.89   194.7 2470.94   201.7 2471.55   229.5 2470.62   252.6 2472.45
   299.9 2471.33     336 2472.15   357.1 2471.49   396.8 2471.44   488.4 2472.42
   527.8 2472.16   553.7 2473.06   570.8 2473.07   590.7 2474.92   599.2 2477.61
     602 2478.03   626.2  2478.7   636.1 2480.42     642 2480.76     698 2482.18
#Mann= 6 ,-1,0
       0      .1       0     160    .045       0   194.7      .1       0
     250     .05       0   561.1     .06       0   681.1     .05       0
#XS Ineff= 2 , 0
                          544.09         2493.82
Permanent Ineff=
       F       F
Bank Sta=160,194.7
XS Rating Curve= 0 ,0
Exp/Cntr(USF)=0,0
Exp/Cntr=0.3,0.1

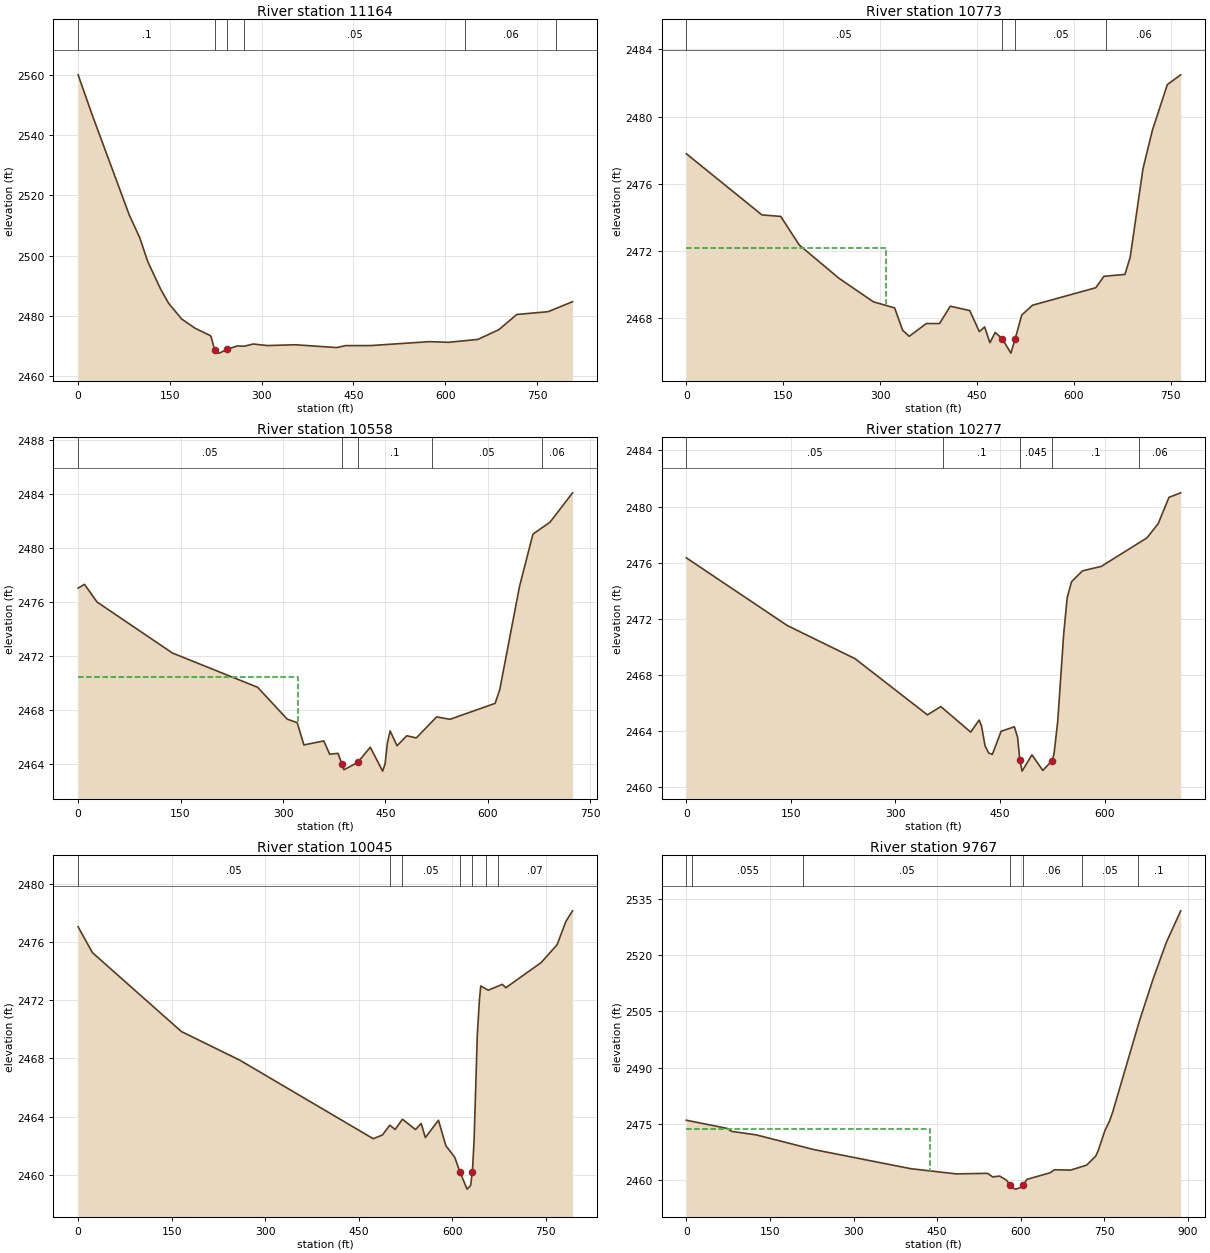
Type RM Length L Ch R = 1 ,11164   ,393,391.1,377.7
XS GIS Cut Line= 3
2284666.07685453491177.3651764672284854.37189558491105.117692354
2285205.51934363490610.857433999
#Sta/Elev= 30
       0 2560.15    23.7 2546.41    83.6  2513.5   100.8 2505.88   113.6 2498.09
   134.5 2488.98   147.9 2484.11   169.3 2478.88     191 2475.84   216.3 2473.34
   217.3 2473.01     223 2468.73   226.1 2467.67     231 2467.54   243.1  2468.8
   260.3 2469.94   271.8 2469.84   286.1 2470.58   309.1 2470.06     355 2470.32
   422.4 2469.39   437.1 2470.03   478.3 2470.06   574.5 2471.36   605.4 2471.14
   653.3  2472.1   687.4 2475.32   716.8  2480.4   768.1 2481.33     808 2484.66
#Mann= 6 ,-1,0
       0      .1       0     223    .045       0   243.1      .1       0
  271.68     .05       0  631.68     .06       0  781.68     .05       0
Bank Sta=223,243.1
XS Rating Curve= 0 ,0
Exp/Cntr=0.3,0.1

Type RM Length L Ch R = 1 ,10773   ,203.6,214.9,218.9
XS GIS Cut Line= 2
2285087.11005204491487.908072768 2285253.7230303490740.957754475
#Sta/Elev= 30
       0 2477.79   117.1 2474.15   146.2 2474.06   174.9 2472.36   236.4 2470.38
   289.7 2468.98   322.5 2468.62   334.9 2467.29   345.1 2466.93   371.6 2467.69
   392.1 2467.69   408.6 2468.72   438.8 2468.46   453.6 2467.21   461.8 2467.49
     470 2466.55   478.2 2467.16   489.1 2466.78   502.5 2465.93   509.2 2466.79
   519.2 2468.19     536 2468.78   633.9 2469.82   646.5  2470.5     679 2470.61
   687.2 2471.65   706.9 2476.89   721.4 2479.17   744.6  2481.9   765.3 2482.48
#Mann= 4 ,-1,0
       0     .05       0   489.1    .045       0   509.2     .05       0
     650     .06       0
#XS Ineff= 2 , 0
          309.68 2472.16
Permanent Ineff=
       F       F
Bank Sta=489.1,509.2
XS Rating Curve= 0 ,0
Exp/Cntr(USF)=0,0
Exp/Cntr=0.3,0.1

Type RM Length L Ch R = 1 ,10558   ,273.3,281.3,283.7
XS GIS Cut Line= 3
2285111.60315386 491489.233485272285200.26915279491334.259628326
2285510.20151023490885.440915827
#Sta/Elev= 30
       0 2477.06     9.3 2477.34    27.7 2476.03   138.1 2472.25   262.9 2469.71
   306.2 2467.35   320.8 2467.09   330.6 2465.44   359.7 2465.74   368.4 2464.75
   380.5 2464.82   386.3 2464.03   389.2  2463.6   409.3 2464.14   427.8 2465.27
   445.9  2463.5   449.5 2464.04   452.9  2465.6   456.9 2466.48     467 2465.38
   481.2 2466.12   495.2 2465.96     525 2467.52   544.5 2467.34   610.6 2468.52
   617.4 2469.54   646.5 2477.22     666 2481.06   691.1 2481.95     724 2484.12
#Mann= 5 ,-1,0
       0     .05       0   386.3    .045       0   409.3      .1       0
  518.55     .05       0  678.55     .06       0
#XS Ineff= 2 , 0
          321.97 2470.48
Permanent Ineff=
       F       F
Bank Sta=386.3,409.3
XS Rating Curve= 0 ,0
Exp/Cntr=0.3,0.1

Type RM Length L Ch R = 1 ,10277   ,231.7,231.7,231.8
XS GIS Cut Line= 3
2285163.55594899491533.014959227 2285426.6944317491441.075007439
 2285699.3439439491108.188975101
#Sta/Elev= 30
       0 2476.35     145 2471.52   242.1 2469.16   345.8 2465.16     365 2465.75
   407.9 2463.93     420 2464.79   423.4 2464.36   428.5 2462.94   433.7 2462.44
   438.9 2462.34   451.5 2463.99   470.5 2464.31   475.1 2463.56  478.342461.926
   481.5 2461.15   495.7 2462.31   511.3  2461.2   524.6  2461.9   527.3 2462.35
   532.7 2464.72   541.2 2470.91   546.2  2473.5   552.5 2474.65   568.1 2475.42
   595.2 2475.74   660.6 2477.77   676.7 2478.78   692.2 2480.66     709 2480.98
#Mann= 5 ,-1,0
       0     .05       0  368.74      .1       0  478.34    .045       0
   524.6      .1       0  648.74     .06       0
Bank Sta=478.34,524.6
XS Rating Curve= 0 ,0
Exp/Cntr(USF)=0,0
Exp/Cntr=0.3,0.1

Type RM Length L Ch R = 1 ,10045   ,256.9,278.2,297.3
XS GIS Cut Line= 3
2285169.74436376491547.4129072152285702.51428706491441.075007439
 2285882.1983511491268.018359334
#Sta/Elev= 30
       0 2477.04    22.9 2475.27   165.6 2469.85   259.4 2467.88   473.2 2462.49
   487.9 2462.75   499.7 2463.42   508.3 2463.13     520 2463.83   540.9 2463.12
     550 2463.54   556.7 2462.57   577.7 2463.76   589.6 2462.01   603.8 2461.22
   612.2  2460.2   623.6 2459.03   629.2 2459.27   632.1 2460.22   634.9 2462.44
     640 2469.62   643.4 2472.03   645.5 2472.98   657.5 2472.69   680.2 2473.09
   685.8 2472.86   742.4 2474.59   767.9 2475.81     782 2477.41   792.7 2478.14
#Mann= 7 ,-1,0
       0     .05       0     500      .1       0     520     .05       0
   612.2    .045       0   632.1     .05       0  653.28     .06       0
  673.28     .07       0
Bank Sta=612.2,632.1
XS Rating Curve= 0 ,0
Exp/Cntr=0.3,0.1

Type RM Length L Ch R = 1 ,9767    ,158.3,154.2,149.1
XS GIS Cut Line= 3
2285183.16639197 491655.597182842285611.16271926491619.138236441
2286056.59593396491722.174389307
#Sta/Elev= 30
       0    2476    73.3 2473.82    81.3 2473.03   125.5 2472.09   228.8 2468.18
   402.5 2463.09     484  2461.7   540.3 2461.85   549.6 2460.89     562 2461.12
   574.3 2460.01   580.6 2458.81   585.5 2457.93   590.7 2457.64   598.9 2458.03
   604.4 2458.86   611.2 2460.25   652.3 2461.99   660.5  2462.8   689.2 2462.71
     718 2464.03   734.4 2466.45   738.8 2467.91   750.8 2473.23   758.9 2475.73
   764.7 2478.15   812.7 2502.45     837 2513.53   860.8 2523.33   886.7 2531.79
#Mann= 7 ,-1,0
       0     .05       0      10    .055       0     210     .05       0
   580.6    .045       0   604.4     .06       0  709.55     .05       0
  809.55      .1       0
#XS Ineff= 2 , 0
          436.25 2473.66
Permanent Ineff=
       F       F
Bank Sta=580.6,604.4
XS Rating Curve= 0 ,0
Exp/Cntr(USF)=0,0
Exp/Cntr=0.3,0.1