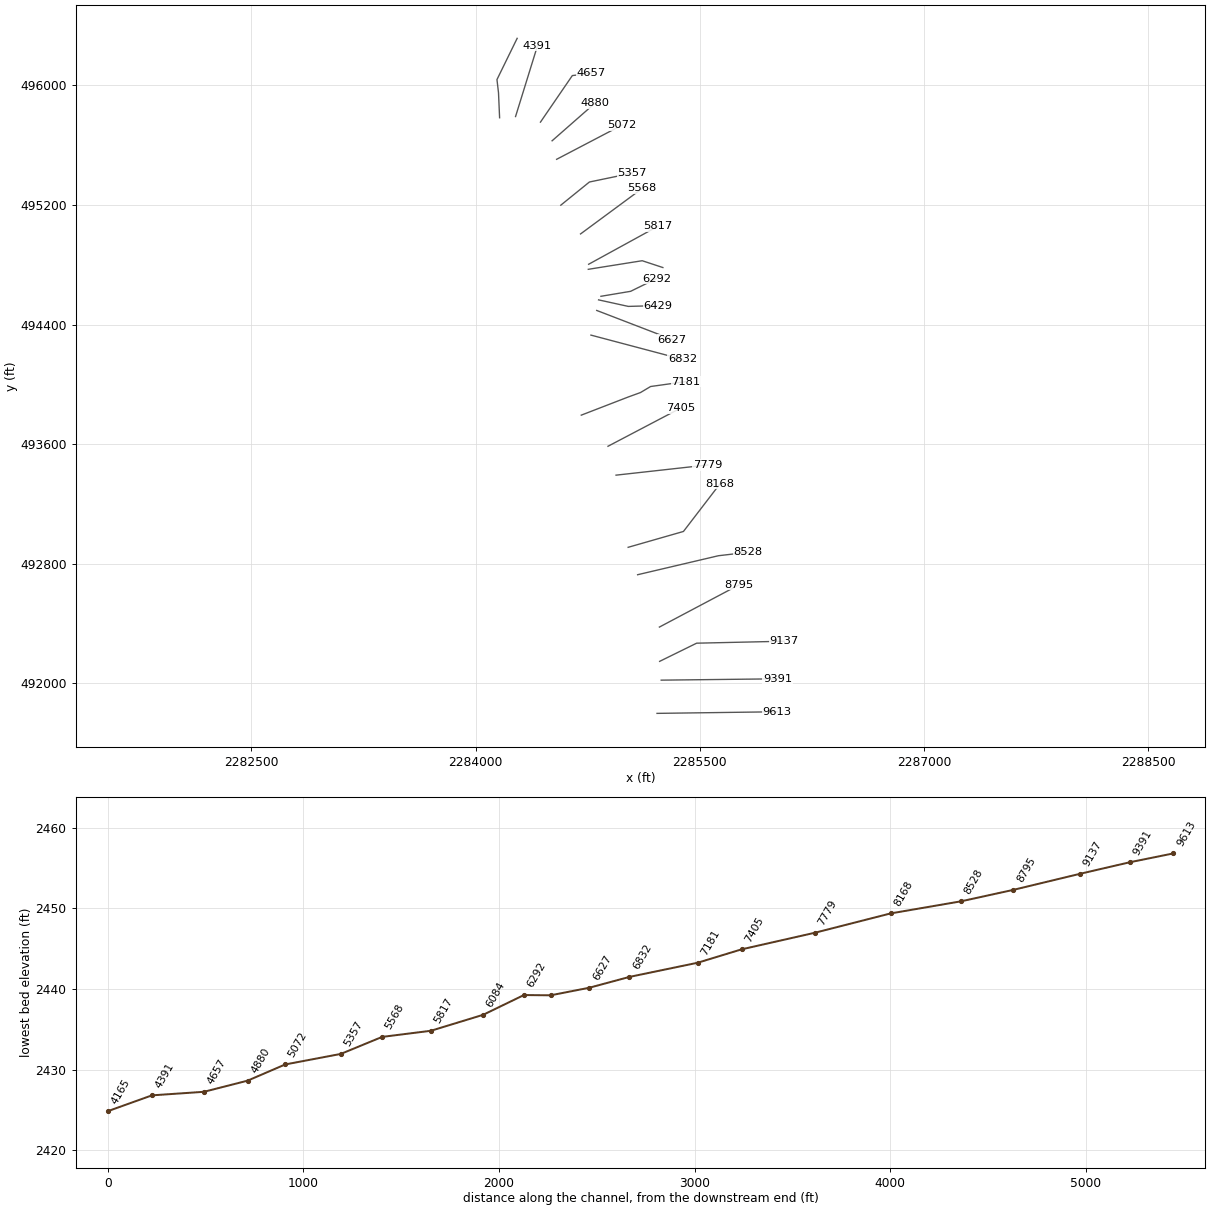
HEC-RAS study THOMASCK.prj: THOMASCK

--- THOMASCK.g01 (geometry) --- (continued)

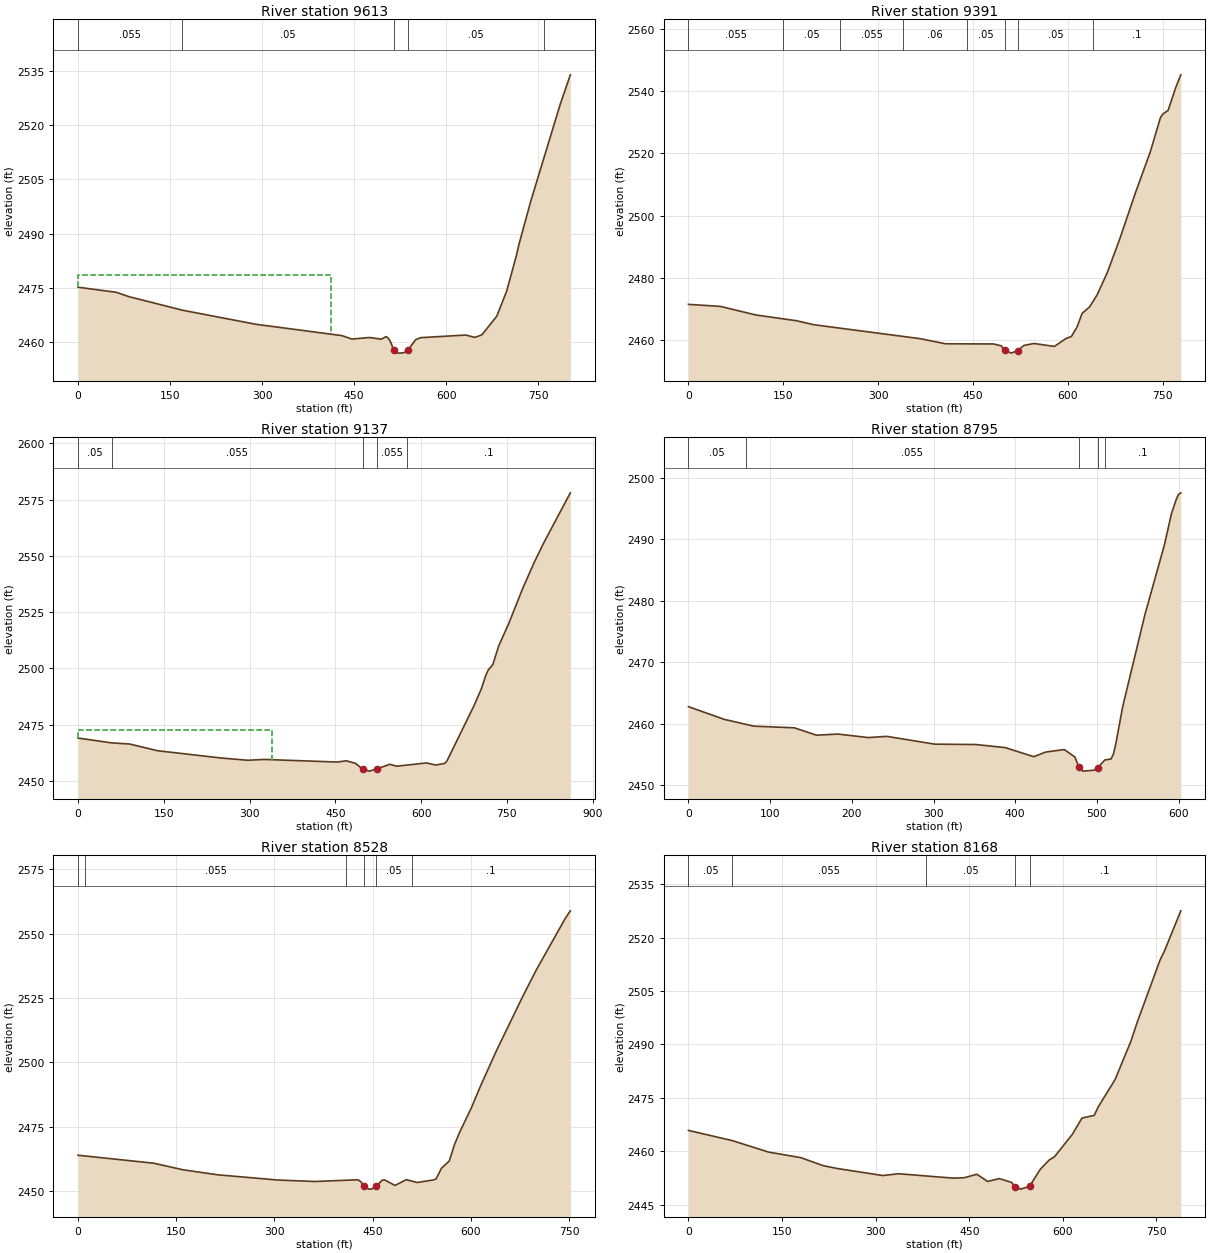
Type RM Length L Ch R = 1 ,9613    ,222,221.7,221.6
XS GIS Cut Line= 2
2285213.78089111491799.0473985462286016.07576201491809.819228852
#Sta/Elev= 30
       0  2475.1    62.4  2473.7    82.4 2472.51   170.4 2468.72   290.4 2464.81
   430.1 2461.68   446.4 2460.72   474.7 2461.15   494.4  2460.7   502.4 2461.41
   506.4  2460.8   510.4 2459.59   514.4 2457.61   518.4 2456.91   522.4 2456.82
   530.4 2456.89   537.4 2457.62   550.4 2460.55   558.4 2461.11   632.1 2461.84
   646.5 2461.19   654.5 2461.65   658.5 2461.94   682.5 2467.07   698.5 2473.95
   714.5 2483.89   718.9 2487.14   738.2 2499.14     786 2525.89   802.4 2534.03
#Mann= 5 ,-1,0
       0    .055       0     170     .05       0   514.4    .045       0
   537.4     .05       0     760      .1       0
#XS Ineff= 2 , 0
          411.67 2478.42
Permanent Ineff=
       F       F
Bank Sta=514.4,537.4
XS Rating Curve= 0 ,0
Exp/Cntr=0.3,0.1

Type RM Length L Ch R = 1 ,9391    ,254.1,254.1,253.4
XS GIS Cut Line= 2
2285241.63766875492021.2750397662286020.24797295492030.224583492
#Sta/Elev= 30
       0 2471.43    50.5 2470.77   106.5 2468.01   170.5 2466.17   198.6 2464.86
   366.6 2460.38   406.6 2458.74   482.6 2458.68   494.6 2458.09   500.7  2456.6
   510.6 2455.73   520.7 2456.57   530.6 2458.21   546.6 2458.84   578.6 2457.88
   597.5 2460.48   605.6 2461.06   614.6 2464.14   622.6 2468.52   634.6 2470.64
   646.6 2474.58   662.6 2481.73   682.6 2492.75   706.8 2507.25   730.6 2520.61
   746.6 2531.59   750.6 2532.73   758.6 2533.86   770.6 2541.17   778.7 2545.31
#Mann= 8 ,-1,0
       0    .055       0     150     .05       0     240    .055       0
     340     .06       0     440     .05       0   500.7    .045       0
   520.7     .05       0     640      .1       0
Bank Sta=500.7,520.7
XS Rating Curve= 0 ,0
Exp/Cntr(USF)=0,0
Exp/Cntr=0.3,0.1

Type RM Length L Ch R = 1 ,9137    ,332.9,342.3,352.8
XS GIS Cut Line= 3
2285231.26725468 492146.93323851  2285478.553502492268.506821462
2286063.79984713492281.651249289
#Sta/Elev= 30
       0 2469.02      59 2466.85    90.2 2466.36   139.2 2463.37   250.6 2460.12
   297.2 2459.13   325.2  2459.5   453.2 2458.34   469.2 2458.89   485.3 2457.74
   497.5 2455.23   509.2  2454.3   522.1 2455.24   545.2 2457.35   557.2 2456.49
   609.3 2457.94   625.3 2457.02   641.3 2457.72   645.3 2458.89   692.6 2483.47
   705.3 2490.93   713.3 2497.04   717.3 2499.26   725.3 2501.66   735.6 2509.95
   753.3 2519.97   777.3 2535.33   797.3 2546.87   813.3 2555.27   860.9 2578.06
#Mann= 5 ,-1,0
       0     .05       0      60    .055       0   497.5    .045       0
   522.1    .055       0  575.56      .1       0
#XS Ineff= 2 , 0
          339.48 2472.43
Permanent Ineff=
       F       F
Bank Sta=497.5,522.1
XS Rating Curve= 0 ,0
Exp/Cntr=0.3,0.1

Type RM Length L Ch R = 1 ,8795    ,272,267.1,262.7
XS GIS Cut Line= 2
2285229.68156353492376.2984890762285762.29921528492658.459030772
#Sta/Elev= 30
       0 2462.79    43.6 2460.73    79.8 2459.62   129.6 2459.35   156.7 2458.15
     183 2458.33   220.1 2457.76   242.7 2457.96   301.4 2456.69   351.7 2456.63
   387.6 2456.13   422.7 2454.65   437.5 2455.41     460 2455.81     473  2454.6
   478.1 2452.93   482.6  2452.3   496.2 2452.44   500.8 2452.85   509.8 2454.12
   517.4 2454.28   520.3 2455.11   523.3 2456.86   531.6 2462.81   558.8 2477.78
   582.5 2489.04   591.3 2494.22   597.3 2496.58     600 2497.33   602.7 2497.59
#Mann= 5 ,-1,0
       0     .05       0      70    .055       0   478.1    .045       0
   500.8    .055       0     510      .1       0
Bank Sta=478.1,500.8
XS Rating Curve= 0 ,0
Exp/Cntr(USF)=0,0
Exp/Cntr=0.3,0.1

Type RM Length L Ch R = 1 ,8528    ,342.5,359.7,373
XS GIS Cut Line= 3
2285083.99262734492726.4159758942285624.38928759492853.435135427
2285819.82989534492876.241568349
#Sta/Elev= 30
       0 2464.03   115.6 2460.93   160.4 2458.38   213.9 2456.42   305.2  2454.4
   361.7 2453.84   427.5 2454.51   431.6 2453.84     437 2452.03     444 2450.88
   448.3  2450.9455.37432452.075   464.9  2454.4   468.6  2454.4   484.1 2452.31
   501.5 2454.56   517.9 2453.45   542.6 2454.43   546.7  2454.8   555.1 2458.99
     567 2461.78     575 2468.17   582.5 2472.74   600.8 2482.44   615.3 2491.21
   639.5 2504.81   679.7 2525.86   699.9 2535.88   744.2  2555.9   751.9 2558.82
#Mann= 6 ,-1,0
       0     .05       0      10    .055       0     410     .05       0
     437    .045       0455.3743     .05       0     510      .1       0
Bank Sta=437,455.3743
XS Rating Curve= 0 ,0
Exp/Cntr=0.3,0.1

Type RM Length L Ch R = 1 ,8168    ,404.4,389.4,373
XS GIS Cut Line= 3
2285020.69565684492909.8149410092285390.49034317493015.773723762
2285636.61361656493336.522640666
#Sta/Elev= 30
       0 2465.86    70.2    2463   128.4 2459.78   180.2 2458.21   215.8 2455.97
   238.4 2455.17   311.5 2453.19   336.5  2453.7     424 2452.47   441.9 2452.58
   462.1 2453.55   479.4 2451.54   498.1 2452.33   517.5 2451.29   523.8 2450.07
   532.4 2449.38   546.6 2450.17   563.8 2454.95     578 2457.54   586.6 2458.47
   615.1 2464.74   630.6 2469.32   650.3 2470.09   656.8 2472.52   683.6  2480.1
   709.1 2490.91   719.2 2496.24   755.4 2513.54   763.5 2516.51     789 2527.51
#Mann= 5 ,-1,0
       0     .05       0      70    .055       0     380     .05       0
   523.8    .045       0   546.6      .1       0
Bank Sta=523.8,546.6
XS Rating Curve= 0 ,0
Exp/Cntr=0.3,0.1

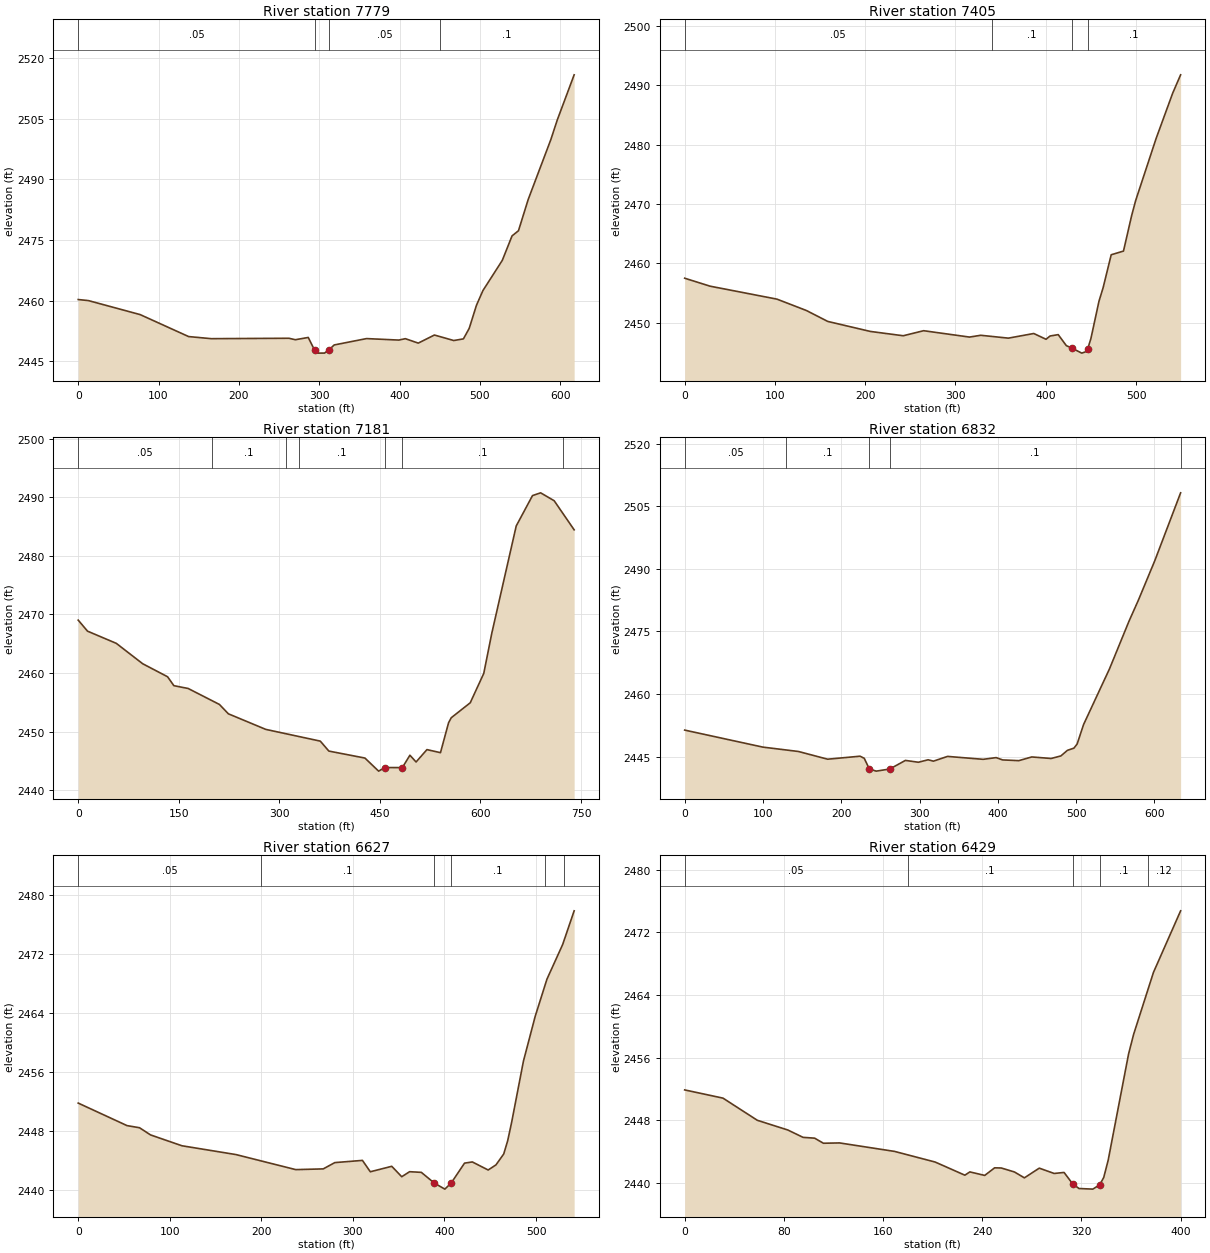
Type RM Length L Ch R = 1 ,7779    ,365.1,373.3,378.7
XS GIS Cut Line= 2
2284939.59516393493392.3934734992285553.05656638493460.555851549
#Sta/Elev= 30
       0 2460.24    12.7 2459.98    77.1 2456.51   137.4 2451.07   165.6 2450.55
   262.2 2450.65   270.2 2450.29   286.3 2450.85   294.1 2447.73   298.4 2446.97
   306.5 2446.98   312.2 2447.79   318.5 2448.99   358.8 2450.57     399  2450.2
   407.1 2450.55   423.2 2449.45   443.3 2451.45   467.4 2450.09   479.4  2450.5
   486.6  2453.1   495.6 2458.81   503.7 2462.47   527.8 2469.95   539.9    2476
   547.9 2477.28     560 2485.01   588.2 2499.86   596.2 2504.71   617.2 2515.89
#Mann= 4 ,-1,0
       0     .05       0   294.1    .045       0   312.2     .05       0
     450      .1       0
Bank Sta=294.1,312.2
XS Rating Curve= 0 ,0
Exp/Cntr(USF)=0,0
Exp/Cntr=0.3,0.1

Type RM Length L Ch R = 1 ,7405    ,223.8,224.3,224.3
XS GIS Cut Line= 2
2284885.77622857493585.6172427582285372.26538725493840.988384709
#Sta/Elev= 30
       0 2457.52    28.1 2456.18   102.2    2454   134.8 2452.09   158.5 2450.25
   205.6 2448.57   242.1 2447.84   264.7 2448.69   315.5 2447.62     328 2447.92
   358.6 2447.44   386.7 2448.22   400.3 2447.25   404.8  2447.8   413.8 2448.03
   422.8 2446.18   429.4 2445.73   439.9 2444.92   445.4 2445.21   446.6 2445.69
     450 2447.36     459 2453.67   463.6 2455.95   472.5 2461.46   486.1 2462.08
   495.1 2468.02   499.6 2470.58   522.2 2480.99   540.6 2488.63   549.4 2491.72
#Mann= 4 ,-1,0
       0     .05       0     340      .1       0   429.4    .045       0
   446.6      .1       0
Bank Sta=429.4,446.6
XS Rating Curve= 0 ,0
Exp/Cntr(USF)=0,0
Exp/Cntr=0.3,0.1

Type RM Length L Ch R = 1 ,7181    ,364,349.1,329.8
XS GIS Cut Line= 5
2284707.19514025493793.7352436562285019.19391814493914.338403928
2285103.35329624493944.9748896392285170.76300418493985.245624251
2285405.70985809494018.057171787
#Sta/Elev= 30
       0 2469.02    13.9 2467.14    56.8 2465.06    96.2 2461.58   133.3 2459.36
   142.7 2457.84     164 2457.36   210.6 2454.64     224 2453.04   279.8 2450.38
   361.1 2448.38   373.9 2446.68   427.7 2445.49   448.1 2443.26   457.6 2443.87
  483.49 2443.86   494.8 2445.97     504 2444.82   520.2 2446.93   540.4 2446.41
   552.5 2451.52   556.5 2452.37   584.8 2454.92     605 2459.94   617.1 2466.86
   653.4 2485.09   677.7 2490.27   689.8 2490.74     710 2489.39   739.8 2484.43
#Mann= 7 ,-1,0
       0     .05       0     200      .1       0     310     .05       0
     330      .1       0   457.6    .045       0  483.49      .1       0
  722.58     .12       0
Bank Sta=457.6,483.49
XS Rating Curve= 0 ,0
Exp/Cntr=0.3,0.1

Type RM Length L Ch R = 1 ,6832    ,211.7,204.6,200.1
XS GIS Cut Line= 2
2284771.67388868494329.0754315352285383.96022578494166.892443434
#Sta/Elev= 30
       0 2451.34    99.8 2447.26   145.3 2446.21   182.6 2444.36     224 2445.08
   229.3 2444.58   235.9    2442   244.7  2441.5     262 2442.01   281.9 2444.07
   298.5 2443.63   310.9 2444.22   317.7 2443.89   335.7 2445.03   381.2 2444.33
   397.8 2444.74     406 2444.19   426.7 2444.01   443.3  2444.9   468.1 2444.53
   480.5 2445.15   488.8 2446.48   497.1 2447.01   501.2 2447.99   509.5 2452.69
   542.6 2466.04   567.4 2477.42   579.4 2482.47   600.5    2492   633.4 2508.24
#Mann= 5 ,-1,0
       0     .05       0     130      .1       0   235.9    .045       0
     262      .1       0   633.4     .12       0
Bank Sta=235.9,262
XS Rating Curve= 0 ,0
Exp/Cntr(USF)=0,0
Exp/Cntr=0.3,0.1

Type RM Length L Ch R = 1 ,6627    ,190.7,198,204.5
XS GIS Cut Line= 2
2284810.43971299494494.0065744642285315.89481559494299.520763379
#Sta/Elev= 30
       0 2451.81    53.3 2448.76      67 2448.47      79  2447.5   113.3 2446.03
   172.2 2444.84   237.6  2442.8   267.6  2442.9   280.2 2443.75   310.4 2444.05
     319 2442.51   342.4 2443.25   353.3 2441.84   361.9 2442.52   374.7 2442.43
   388.9 2440.98   400.4 2440.16   407.4    2441   421.9 2443.68   430.4 2443.84
   447.7 2442.75   456.2 2443.44   464.7 2444.92     469 2446.71   473.3 2449.18
   486.2 2457.48     499 2463.53   511.9 2468.59     529 2473.26   541.6 2477.84
#Mann= 6 ,-1,0
       0     .05       0     200      .1       0   388.9    .045       0
   407.4      .1       0     510     .12       0     530      .1       0
Bank Sta=388.9,407.4
XS Rating Curve= 0 ,0
Exp/Cntr(USF)=0,0
Exp/Cntr=0.3,0.1

Type RM Length L Ch R = 1 ,6429    ,126.9,136.9,145
XS GIS Cut Line= 3
2284822.92008589494564.7286875862285021.56602128494521.047382422
2285218.13189451494526.247537799
#Sta/Elev= 30
       0 2451.89    30.9 2450.84    58.6 2448.01    83.2 2446.77    95.5 2445.83
   104.8 2445.73   111.9 2445.08   124.9 2445.12   169.2 2444.04     202 2442.68
     226    2441     230 2441.42     242 2440.97     250 2441.94   255.3 2441.92
     266 2441.41     274 2440.66     286  2441.9     298 2441.22     306 2441.35
   312.8 2439.92     318  2439.3   329.2 2439.22   334.7 2439.77     338 2440.71
   341.6 2442.93     358 2456.46   362.1 2458.99   378.1  2466.9     400 2474.76
#Mann= 5 ,-1,0
       0     .05       0     180      .1       0   312.8    .045       0
   334.7      .1       0  373.39     .12       0
Bank Sta=312.8,334.7
XS Rating Curve= 0 ,0
Exp/Cntr(USF)=0,0
Exp/Cntr=0.3,0.1

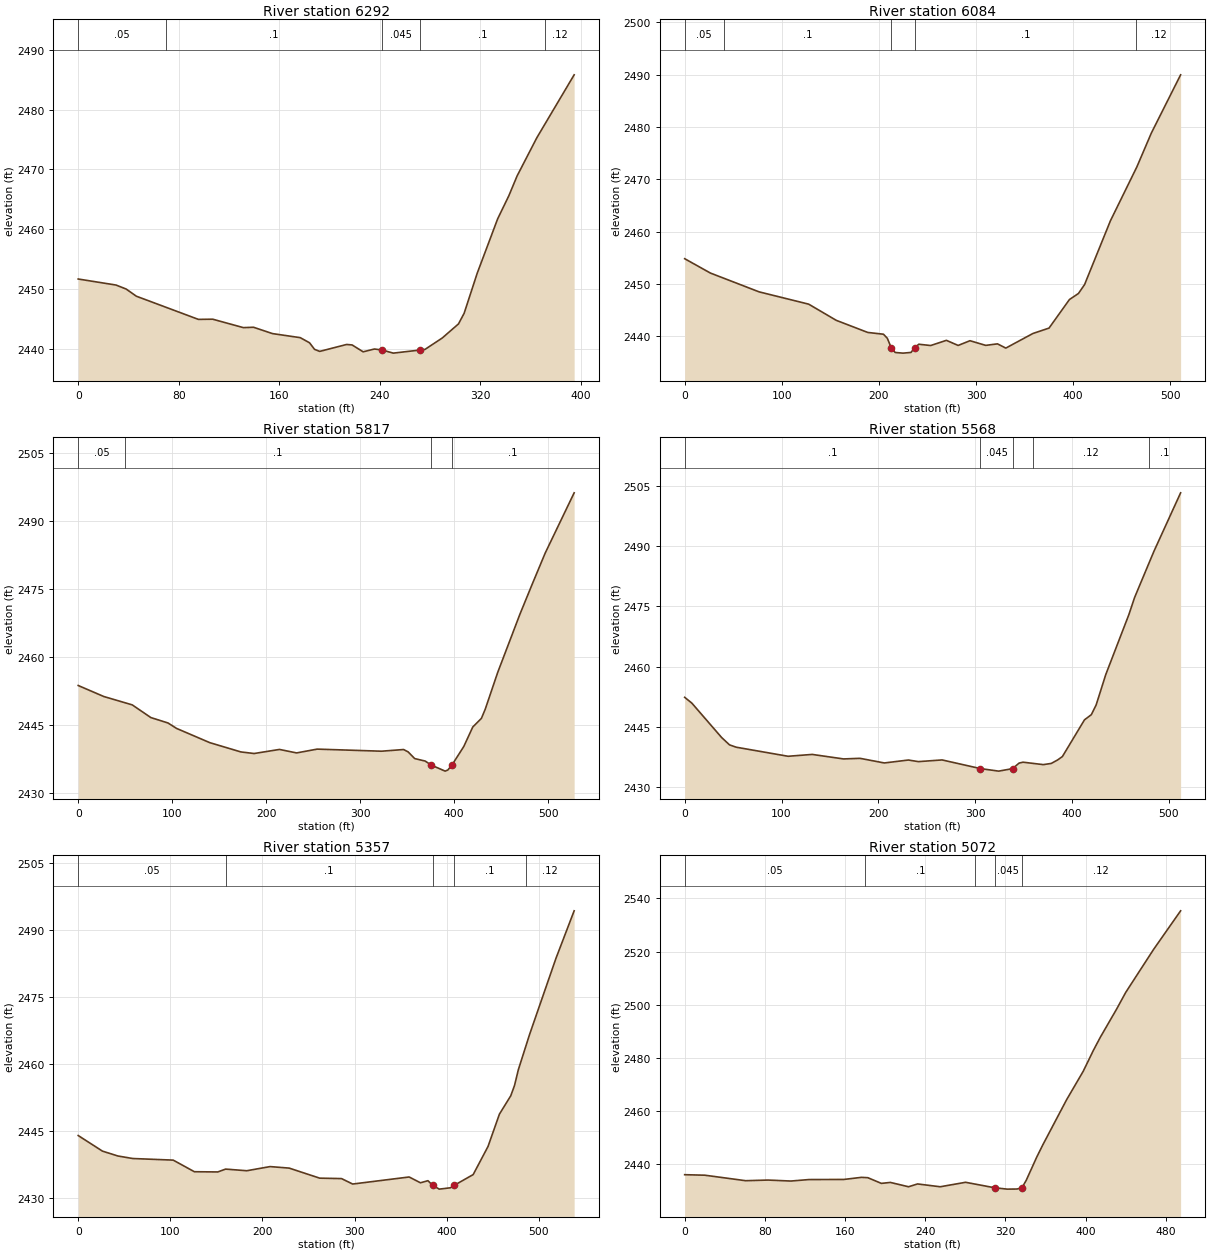
Type RM Length L Ch R = 1 ,6292    ,212.3,208.3,200.7
XS GIS Cut Line= 3
2284838.52055202494588.6494023182285037.16648741494621.930396729
2285210.85167699494707.212944905
#Sta/Elev= 30
       0 2451.66    30.1 2450.65    38.2 2449.98    46.3 2448.78    95.7  2444.9
   107.1 2444.93   131.5 2443.52   139.6 2443.58   154.7 2442.52   176.8 2441.84
   184.2 2440.98   188.2 2439.88   192.3 2439.54   213.7  2440.7   218.1 2440.62
   226.9 2439.47   235.9 2439.94     242 2439.77   250.9 2439.25   272.3 2439.77
   276.1 2439.87   289.8 2441.77   302.8 2444.14   307.3 2445.92   317.7 2452.62
     334 2461.74   342.9  2465.6   349.5 2468.93   365.2 2475.32   394.9 2485.85
#Mann= 5 ,-1,0
       0     .05       0      70      .1       0     242    .045       0
   272.3      .1       0  371.41     .12       0
Bank Sta=242,272.3
XS Rating Curve= 0 ,0
Exp/Cntr(USF)=0,0
Exp/Cntr=0.3,0.1

Type RM Length L Ch R = 1 ,6084    ,260.6,267.1,272.6
XS GIS Cut Line= 3
2284754.04840152494769.1284630032285114.61522624494826.595129891
2285252.87395149494780.982601611
#Sta/Elev= 30
       0 2454.83    26.5 2452.09    76.6  2448.5   127.7 2446.15   156.1 2443.06
   188.5 2440.75   204.7 2440.41   208.7 2439.63   212.8 2437.77   216.8 2436.92
   224.9  2436.8     233 2436.93   236.72437.787   241.1  2438.5   253.3 2438.25
   269.5 2439.24   281.6 2438.27   293.8 2439.17     310 2438.28   322.1 2438.57
   330.7 2437.76   358.6 2440.55   375.2 2441.58   396.2 2447.03   405.5 2448.19
   411.8 2449.89   438.4 2462.06   465.7 2472.38   480.5  2478.8   510.7 2489.94
#Mann= 5 ,-1,0
       0     .05       0      40      .1       0   212.8    .045       0
   236.7      .1       0  465.12     .12       0
Bank Sta=212.8,236.7
XS Rating Curve= 0 ,0
Exp/Cntr=0.3,0.1

Type RM Length L Ch R = 1 ,5817    ,246.1,249.2,252.3
XS GIS Cut Line= 2
2284756.35809707494802.8958038342285219.17192559495056.663386212
#Sta/Elev= 30
       0 2453.73    27.2  2451.3    57.5 2449.45    77.3 2446.65    95.6 2445.45
   104.7 2444.25     140 2441.11   173.1 2439.06   187.2 2438.71   214.2 2439.61
   232.4 2438.84   254.3 2439.68   322.7 2439.22   346.3 2439.59   351.1 2439.07
   358.1 2437.59   369.3 2437.04   375.7 2436.16   390.5 2434.82   393.4 2435.07
   397.8 2436.18   410.4 2440.28   419.9 2444.56   429.1 2446.47   433.2 2448.51
   446.4 2456.59     470 2469.43   483.3 2476.17     497 2482.98   527.8 2496.28
#Mann= 4 ,-1,0
       0     .05       0      50      .1       0   375.7    .045       0
   397.8      .1       0
Bank Sta=375.7,397.8
XS Rating Curve= 0 ,0
Exp/Cntr(USF)=0,0
Exp/Cntr=0.3,0.1

Type RM Length L Ch R = 1 ,5568    ,221.9,211.1,198.9
XS GIS Cut Line= 2
2284702.22262463495005.6699745142285114.38437603495309.817579252
#Sta/Elev= 30
       0  2452.4     7.4 2450.96    38.2  2442.4    46.3 2440.59    53.1 2440.01
   106.8 2437.75   131.7 2438.21   164.1 2437.09   181.1 2437.24   206.2 2436.09
   231.1 2436.82   241.3 2436.42   265.9 2436.84305.51332434.686   324.3 2434.06
   338.6 2434.68   345.4 2436.06   349.5 2436.28   370.3 2435.68   378.6 2435.97
   385.2 2436.84   390.1 2437.68   412.9  2446.8     420 2448.09     425 2450.53
   434.9 2458.06   458.7 2472.91   464.7 2477.22   484.6 2488.66   512.2 2503.21
#Mann= 5 ,-1,0
       0      .1       0305.5133    .045       0   338.6      .1       0
     360     .12       0     480      .1       0
Bank Sta=305.5133,338.6
XS Rating Curve= 0 ,0
Exp/Cntr=0.3,0.1

Type RM Length L Ch R = 1 ,5357    ,278.2,284.7,291
XS GIS Cut Line= 3
2284570.19253459495198.1076124562284761.55825245495353.072242678
2285047.56679816495412.354013972
#Sta/Elev= 30
       0 2443.96    26.3 2440.47      43 2439.38    59.2 2438.81   103.1 2438.45
   126.1 2435.85   151.5  2435.8     160 2436.44   182.9 2436.07   208.3    2437
     229 2436.66   262.1 2434.41   285.8 2434.31   297.9 2433.09   359.2 2434.67
   371.5 2433.37   379.6 2433.84   384.7  2432.8   391.9 2431.95   404.1 2432.25
   408.2 2432.81   428.7 2435.21   444.8  2441.5   457.2 2448.76   469.5 2452.87
   473.6 2455.19   477.7 2458.69   489.9  2466.6   518.5 2483.64   538.3 2494.32
#Mann= 5 ,-1,0
       0     .05       0     160      .1       0   384.7    .045       0
   408.2      .1       0  486.24     .12       0
Bank Sta=384.7,408.2
XS Rating Curve= 0 ,0
Exp/Cntr(USF)=0,0
Exp/Cntr=0.3,0.1

Type RM Length L Ch R = 1 ,5072    ,186.6,192.2,197.9
XS GIS Cut Line= 2
2284542.32944377495504.8842175272284980.66503913495734.259059024
#Sta/Elev= 30
       0 2436.07    20.1 2435.88    60.8 2433.81    83.3 2434.05   105.9 2433.68
     124 2434.24   158.7 2434.28   176.4 2435.07   182.7 2434.94   196.2  2432.8
   205.2 2433.16   223.3 2431.53   232.3 2432.59   254.9 2431.53   280.2 2433.21
   309.1 2431.16   321.7 2430.64   331.6 2430.68   336.5  2431.2   340.7 2433.96
   351.3 2442.79   357.2 2447.26   380.9 2464.23   397.5 2474.95   407.6 2482.78
   414.7 2487.85     431 2498.47     440 2504.69   467.7 2520.81   494.7 2535.35
#Mann= 5 ,-1,0
       0     .05       0     180      .1       0     290     .12       0
   309.1    .045       0   336.5     .12       0
Bank Sta=309.1,336.5
XS Rating Curve= 0 ,0
Exp/Cntr=0.3,0.1

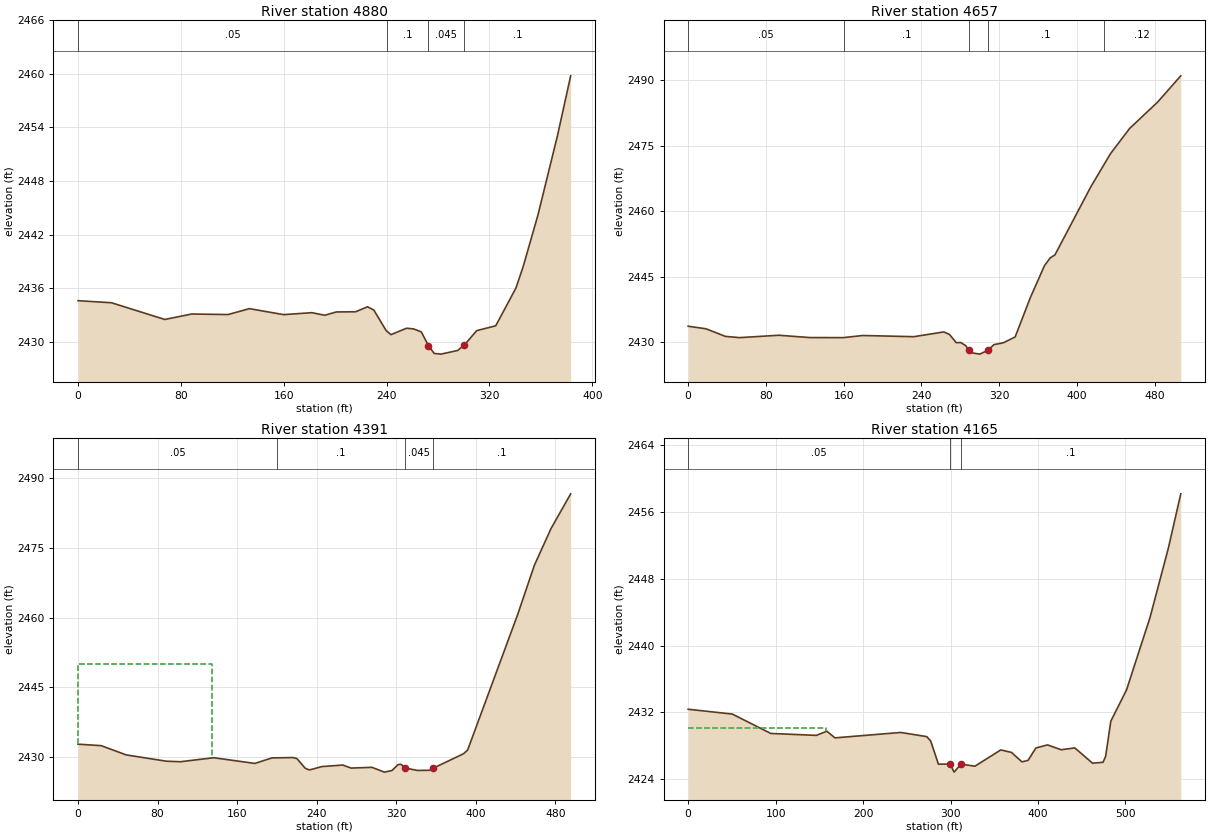
Type RM Length L Ch R = 1 ,4880    ,218.9,223.1,227.2
XS GIS Cut Line= 2
2284511.95079437495628.6804776382284800.03940223495881.408028941
#Sta/Elev= 30
       0 2434.61      26 2434.38    67.5 2432.51    88.4 2433.12   116.7 2433.06
   133.3 2433.72   159.9 2433.05   181.9 2433.27   191.9 2432.98   200.9 2433.35
   215.9 2433.37   225.2 2433.93   230.1 2433.56   239.7 2431.26   243.4 2430.81
   255.6 2431.53     261 2431.45     267 2431.12   272.6 2429.57     277 2428.71
   282.3 2428.63   295.3 2429.04   300.5 2429.65   310.1 2431.26   324.9  2431.8
   340.6 2436.02   346.2  2438.4   357.7 2444.18   372.8    2453   383.2 2459.78
#Mann= 4 ,-1,0
       0     .05       0     240      .1       0   272.6    .045       0
   300.5      .1       0
Bank Sta=272.6,300.5
XS Rating Curve= 0 ,0
Exp/Cntr(USF)=0,0
Exp/Cntr=0.3,0.1

Type RM Length L Ch R = 1 ,4657    ,258.3,265.6,271.5
XS GIS Cut Line= 3
2284434.14847485495753.5910087162284647.31572345496064.973062151
   2284775.92089 496079.60731568
#Sta/Elev= 30
       0 2433.65    18.4 2433.06    38.3 2431.32    52.8 2431.03    93.2 2431.58
   124.9 2431.05   159.5 2431.03   179.6 2431.52   232.2 2431.25     263 2432.34
   268.8 2431.78   275.8 2429.87   280.3 2429.92   285.5  2429.2   288.9 2428.17
   291.8 2427.55     300 2427.25   308.1  2428.1   314.6 2429.43   324.3 2429.85
   336.4 2431.19   352.2 2440.29   366.6 2447.55   372.4  2449.3   377.4 2450.03
   414.4 2465.68   434.6 2473.25   454.2 2479.01   482.9 2485.03   506.8 2491.07
#Mann= 5 ,-1,0
       0     .05       0     160      .1       0   288.9    .045       0
   308.1      .1       0  427.36     .12       0
Bank Sta=288.9,308.1
XS Rating Curve= 0 ,0
Exp/Cntr=0.3,0.1

Type RM Length L Ch R = 1 ,4391    ,219.9,226.5,223.6
XS GIS Cut Line= 2
2284267.54349167495790.9253253882284414.18787329496264.139464659
#Sta/Elev= 30
       0 2432.81    23.3 2432.49    48.4 2430.51    88.6 2429.16   102.9 2429.04
   136.4  2429.9   177.8 2428.68     195 2429.86   215.9 2429.94   220.1 2429.72
   228.5 2427.63   232.7 2427.28   245.2    2428   266.2 2428.33   274.6 2427.68
   295.5 2427.84   308.1 2426.81   315.6 2427.15     322 2428.45   324.8 2428.48
     329  2427.7   341.2 2427.17     354 2427.21   357.2 2427.66   387.6 2430.75
   391.8 2431.56   442.1 2460.64   458.8 2471.16   475.6 2479.08   495.4 2486.55
#Mann= 4 ,-1,0
       0     .05       0     200      .1       0     329    .045       0
   357.2      .1       0
#XS Ineff= 2 , 0
          135.18 2449.98
Permanent Ineff=
       F       F
Bank Sta=329,357.2
XS Rating Curve= 0 ,0
Exp/Cntr(USF)=0,0
Exp/Cntr=0.3,0.1

Type RM Length L Ch R = 1 ,4165    ,115.1,112.9,111.1
XS GIS Cut Line= 4
2284160.86561363495782.7628758632284153.52813059495950.057489229
2284143.25565433496038.1072857382284278.26534231496313.996648131
#Sta/Elev= 30
       0 2432.37    50.5 2431.79    94.5 2429.47   146.6 2429.24   158.6 2429.74
   167.9 2428.94   243.1 2429.59   272.9 2429.09   277.3 2428.57   286.2 2425.79
   299.6 2425.81   304.1 2424.84  311.85  2425.8   327.9 2425.55   357.5  2427.5
   369.7  2427.2   381.7 2426.07   388.7 2426.25   397.6 2427.73   410.9  2428.1
   426.5 2427.52   442.1 2427.74   462.4 2425.91   474.4 2426.02   477.4 2426.74
   483.3 2430.94   501.3 2434.69   528.2 2443.38     549 2451.62   563.3 2458.16
#Mann= 3 ,-1,0
       0     .05       0   299.6    .045       0  311.85      .1       0
#XS Ineff= 2 , 0
          157.87 2430.18
Permanent Ineff=
       F       F
Bank Sta=299.6,311.85
XS Rating Curve= 0 ,0
Exp/Cntr(USF)=0,0
Exp/Cntr=0.3,0.1