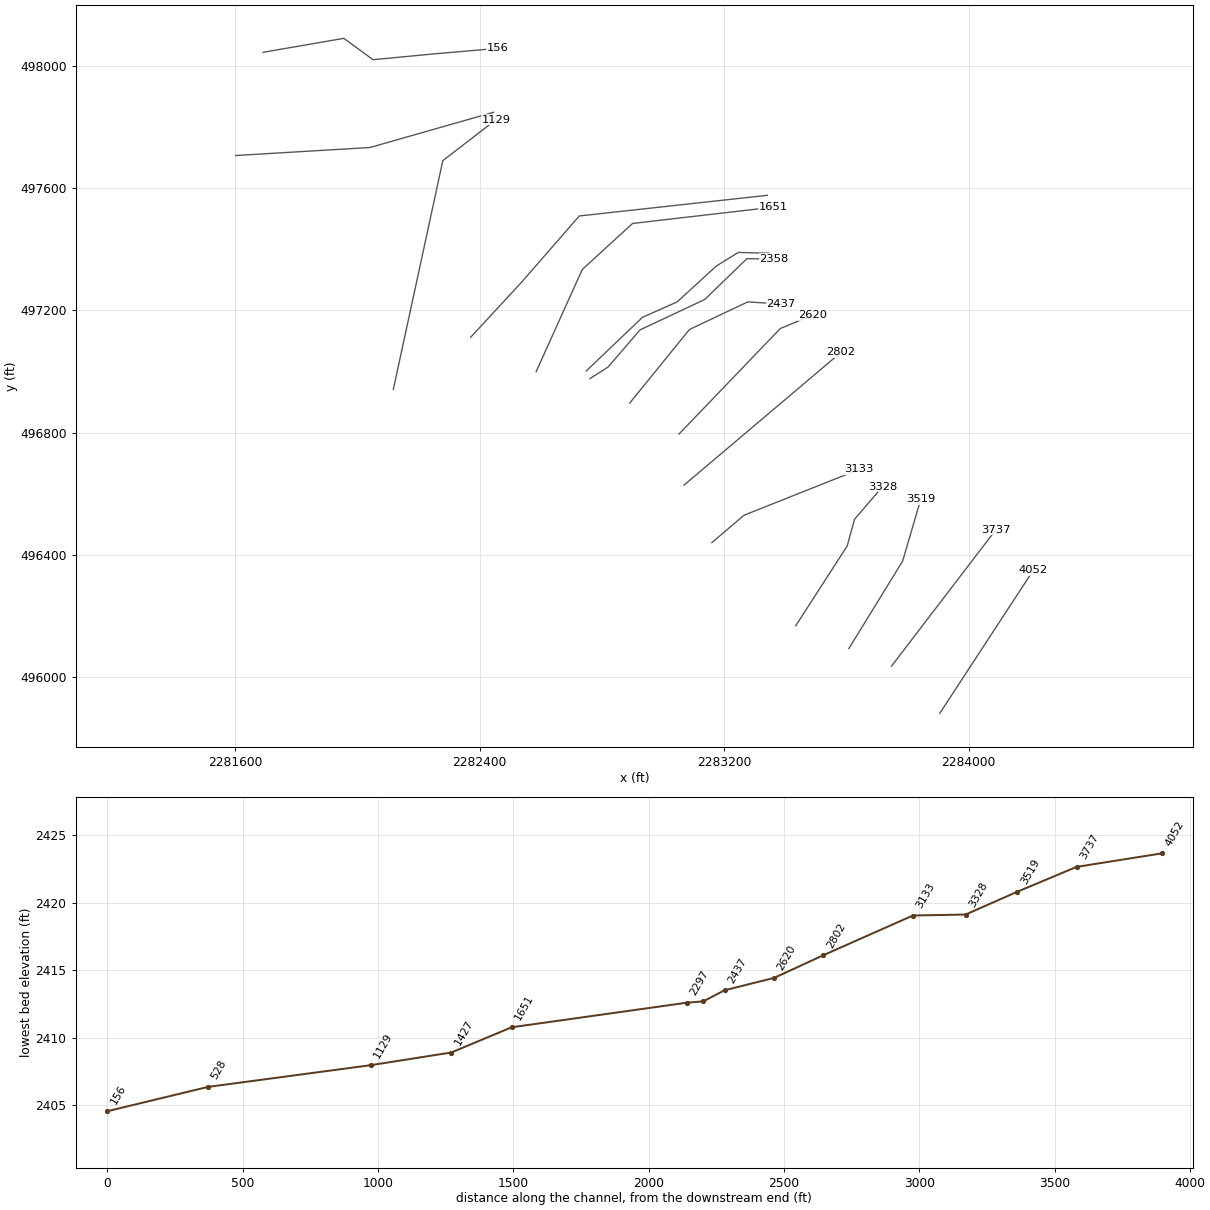
HEC-RAS study THOMASCK.prj: THOMASCK

--- THOMASCK.g01 (geometry) --- (continued)

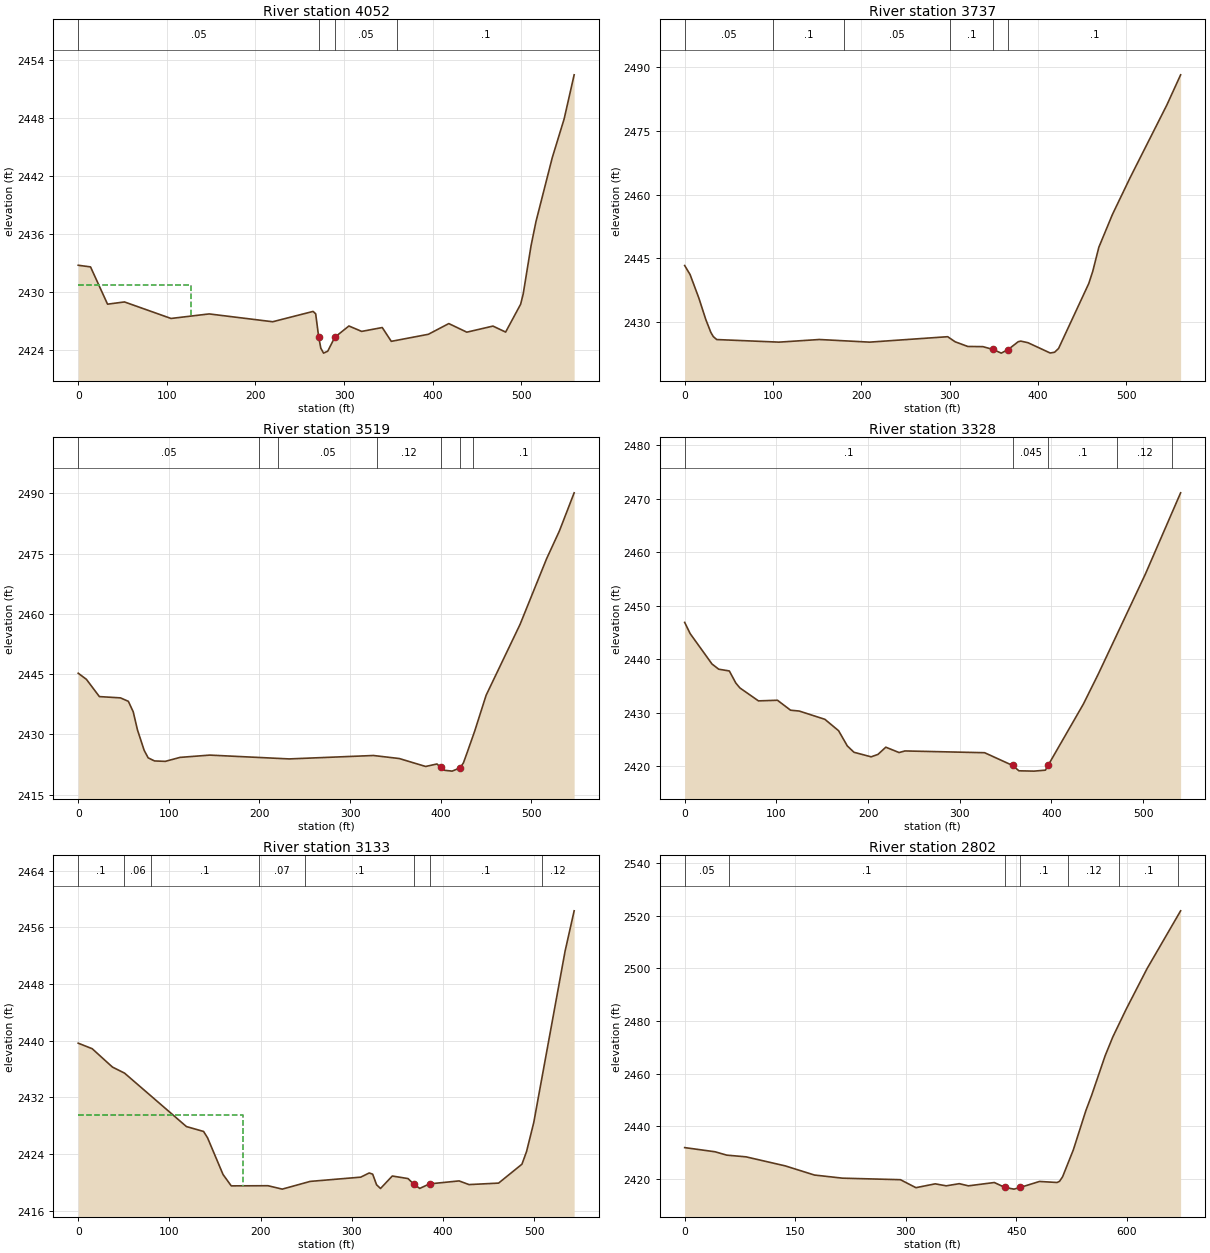
Type RM Length L Ch R = 1 ,4052    ,308.7,314.1,306.4
XS GIS Cut Line= 2
2283905.07235613495881.5035736622284211.13543818496349.816587968
#Sta/Elev= 30
       0 2432.76    13.9 2432.59    33.1 2428.73    52.2 2428.96   104.7 2427.25
   147.7 2427.72   219.4 2426.91     265 2427.98   267.9 2427.73   271.32425.334
   273.7 2424.17   276.8 2423.66   281.5 2423.86  289.492425.304   305.4 2426.47
   319.8 2425.91     343 2426.31   353.2 2424.88     395 2425.61   418.1 2426.72
   438.4 2425.83   467.9 2426.46   482.2 2425.84   499.1 2428.72     502 2429.78
   510.9 2434.79   516.4 2437.27   534.8  2443.9   548.2 2447.91   559.5 2452.48
#Mann= 4 ,-1,0
       0     .05       0   271.3    .045       0  289.49     .05       0
     360      .1       0
#XS Ineff= 2 , 0
          127.44 2430.68
Permanent Ineff=
       F       F
Bank Sta=271.3,289.49
XS Rating Curve= 0 ,0
Exp/Cntr=0.3,0.1

Type RM Length L Ch R = 1 ,3737    ,210.4,218.9,225.4
XS GIS Cut Line= 2
2283747.52795401496036.3726591642284088.65814672496482.545990476
#Sta/Elev= 30
       0  2443.3     6.1 2441.19    16.1 2435.61    23.9 2430.59    29.6 2427.56
    32.4 2426.56    36.3 2425.86   106.8 2425.25   152.5 2425.87   209.3 2425.25
   297.8 2426.53   306.4 2425.32   320.6 2424.23   337.7 2424.19   349.2 2423.52
   358.5 2422.66   366.3 2423.51   377.7 2425.35   380.6 2425.49   388.7 2425.12
   413.9 2422.69   418.9 2422.87   423.4 2423.76   457.6 2439.07   462.1 2441.94
     469 2447.61   484.4 2455.35   504.5 2464.05   546.1 2481.18   561.6 2488.25
#Mann= 6 ,-1,0
       0     .05       0     100      .1       0     180     .05       0
     300      .1       0   349.2    .045       0   366.3      .1       0
Bank Sta=349.2,366.3
XS Rating Curve= 0 ,0
Exp/Cntr(USF)=0,0
Exp/Cntr=0.3,0.1

Type RM Length L Ch R = 1 ,3519    ,191.1,191,188
XS GIS Cut Line= 3
2283607.76140436496093.4785508272283783.74613228 496379.79869643
2283843.11241424496582.412729328
#Sta/Elev= 30
       0  2445.2    9.04 2443.68   23.35 2439.38   46.62 2439.06   55.33  2438.2
   60.69  2435.6   65.38 2431.09   72.78 2425.99   77.18 2424.13   84.16 2423.36
   96.04 2423.25  112.33 2424.24   145.2 2424.81  232.71 2423.86  325.76 2424.71
  354.19 2423.96  383.37 2421.98  395.87  2422.6  400.04 2421.74  404.21 2421.03
  412.55 2420.82  421.35 2421.63  425.05 2422.88  429.22 2425.49  437.47 2430.78
  450.06  2439.7  487.57 2457.38  516.75 2473.68  530.96 2480.64  547.21 2490.12
#Mann= 7 ,-1,0
       0     .05       0     200      .1       0     220     .05       0
     330     .12       0  400.04    .045       0  421.35     .12       0
  436.08      .1       0
Bank Sta=400.04,421.35
XS Rating Curve= 0 ,0
Exp/Cntr=0.3,0.1

Type RM Length L Ch R = 1 ,3328    ,214.5,194.6,172.6
XS GIS Cut Line= 4
2283433.95217709496168.1078301812283602.29681835496429.193231888
2283626.49006021496516.8937336192283717.21471717496622.739166744
#Sta/Elev= 30
       0 2446.91       6 2444.81    29.8 2439.14    37.1 2438.17    48.7 2437.84
    55.8 2435.58    60.3 2434.66    80.5 2432.25   101.2 2432.37   115.5 2430.51
     125 2430.35   152.9 2428.81   167.9 2426.68   177.4 2423.84   184.7 2422.65
   203.4  2421.8   210.8 2422.25   219.4  2423.6   233.9  2422.6   240.3  2422.9
   327.2 2422.57   357.7 2420.19   364.6 2419.19   381.2 2419.13   393.5 2419.31
   396.7 2420.29     435 2431.68   451.3  2437.3   502.6 2455.95     541 2471.11
#Mann= 5 ,-1,0
       0      .1       0   357.7    .045       0   396.7      .1       0
  471.63     .12       0  531.63      .1       0
Bank Sta=357.7,396.7
XS Rating Curve= 0 ,0
Exp/Cntr(USF)=0,0
Exp/Cntr=0.3,0.1

Type RM Length L Ch R = 1 ,3133    ,321.8,330.8,335.6
XS GIS Cut Line= 3
2283159.59929398496440.2559179542283264.84938096496529.923660635
2283641.33098257496679.783106869
#Sta/Elev= 30
       0 2439.66    15.3 2438.88    37.5 2436.29    50.8 2435.43   118.6 2427.89
   137.4  2427.2   141.8 2426.29   158.7 2421.13   167.7 2419.52     208 2419.54
   223.6 2419.06   254.2 2420.15   309.6 2420.75   318.9 2421.34   322.7 2421.17
     327 2419.67   331.3 2419.15   344.2 2420.91   361.4 2420.55   368.1 2419.73
   374.3 2419.16     385  2419.8   417.4 2420.22   428.3  2419.7   460.7 2419.91
   486.3 2422.58   491.3 2424.35   499.2 2428.44   533.6 2452.67   543.5 2458.34
#Mann= 8 ,-1,0
       0      .1       0      50     .06       0      80      .1       0
  198.27     .07       0  248.27      .1       0   368.1    .045       0
     385      .1       0  508.27     .12       0
#XS Ineff= 2 , 0
          180.65 2429.58
Permanent Ineff=
       F       F
Bank Sta=368.1,385
XS Rating Curve= 0 ,0
Exp/Cntr=0.3,0.1

Type RM Length L Ch R = 1 ,2802    ,178.8,181.8,183.4
XS GIS Cut Line= 2
2283068.62985205496628.5031865042283582.35518981 497063.22042195
#Sta/Elev= 30
       0 2431.89    41.3  2430.3      57 2429.03    83.2 2428.38   136.4 2424.95
   176.1 2421.47   214.2 2420.28   292.8  2419.7   313.8 2416.67     340 2418.13
   354.9 2417.37   372.6 2418.19     385 2417.37   420.2 2418.63   434.5 2416.77
   446.9 2416.12   455.3 2416.76   481.5 2419.03   505.4 2418.64   508.8 2419.12
   512.9 2420.85   527.4 2431.02   544.4 2445.92   552.2 2451.72   570.6 2466.79
     581 2473.92     599 2484.38   627.4 2499.82     670 2520.36     673  2521.8
#Mann= 7 ,-1,0
       0     .05       0      60      .1       0   434.5    .045       0
   455.3      .1       0     520     .12       0     590      .1       0
     670     .12       0
Bank Sta=434.5,455.3
XS Rating Curve= 0 ,0
Exp/Cntr(USF)=0,0
Exp/Cntr=0.3,0.1

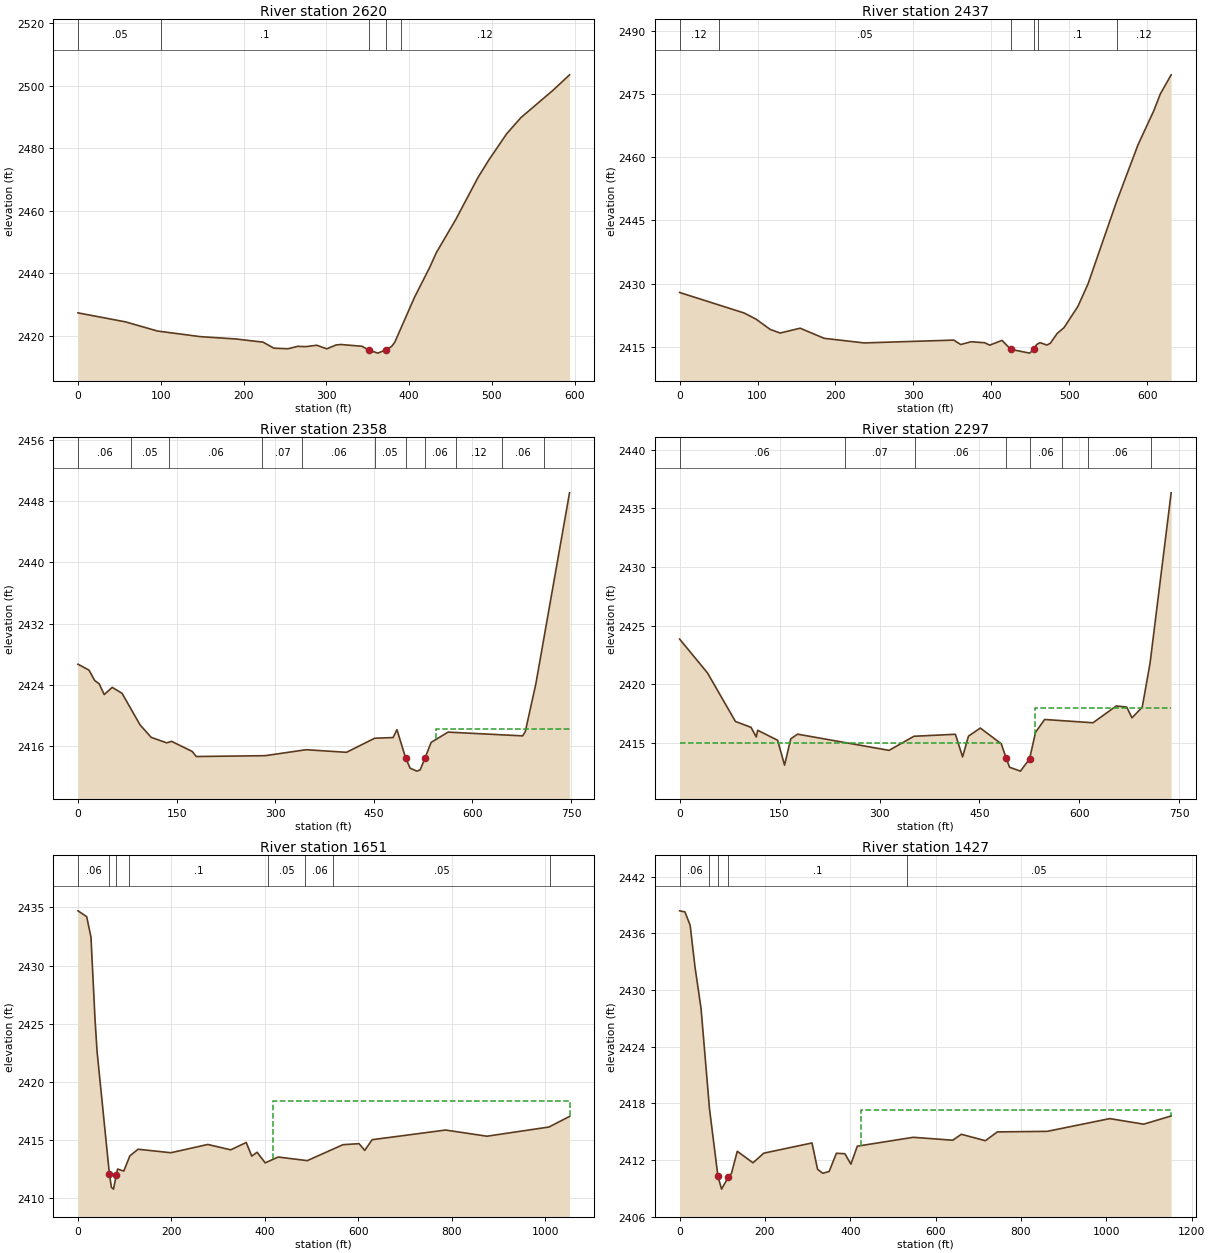
Type RM Length L Ch R = 1 ,2620    ,190.8,183.5,174.1
XS GIS Cut Line= 3
2283052.43361033496795.8743449552283383.88212743497141.268310753
 2283490.3369658497185.062898058
#Sta/Elev= 30
       0 2427.31    57.3 2424.44    96.1  2421.5   147.8 2419.71   190.3 2418.97
   223.6 2417.95   236.5 2416.03   253.8 2415.84   265.4 2416.61   275.2 2416.52
   288.5 2416.96   300.6 2415.81   311.9 2417.07   317.8 2417.19   343.1 2416.63
   351.1 2415.45   362.2 2414.44  372.412415.528   378.8 2416.56   382.7 2417.93
   406.5 2432.28   425.1 2441.97   432.9 2446.57   456.4 2457.18   483.3 2470.63
   496.3 2476.18   517.9 2484.59   535.2 2489.77   573.9 2498.49   593.8 2503.42
#Mann= 5 ,-1,0
       0     .05       0     100      .1       0   351.1    .045       0
  372.41      .1       0     390     .12       0
Bank Sta=351.1,372.41
XS Rating Curve= 0 ,0
Exp/Cntr=0.3,0.1

Type RM Length L Ch R = 1 ,2437    ,73,78.4,84.2
BEGIN DESCRIPTION:
structure xs 4
END DESCRIPTION:
XS GIS Cut Line= 4
2282890.96976889 496897.084100682283086.50060812497137.929308646
2283277.43390797 497228.248271482283386.63717087497220.968053953
#Sta/Elev= 30
       0  2427.9    82.6 2423.05      98 2421.59   116.1 2419.16   128.9 2418.28
   154.7 2419.43   185.6 2417.03   236.9 2415.94   351.9 2416.61   360.8 2415.56
     374 2416.22   391.7 2415.98     398 2415.41   413.8 2416.54425.0382 2414.42
   449.2 2413.52454.96822414.415   458.1 2415.54   462.5 2416.01   471.4 2415.44
   475.8 2415.86   484.6 2418.18   493.5 2419.59   511.2  2424.6   524.2 2429.93
   560.7 2449.37   588.3 2462.89   608.4  2470.9   617.1 2475.01   630.9 2479.51
#Mann= 6 ,-1,0
       0     .12       0      50     .05       0425.0382    .045       0
454.9682     .05       0  460.22      .1       0  561.44     .12       0
Bank Sta=425.0382,454.9682
XS Rating Curve= 0 ,0
Exp/Cntr(USF)=0,0
Exp/Cntr=0.5,0.3

Type RM Length L Ch R = 1 ,2358    ,60,61.4,62.7
BEGIN DESCRIPTION:
structure xs 3
END DESCRIPTION:
XS GIS Cut Line= 6
2282760.99418584496977.2860215332282820.22687201497014.863747164
2282924.68021105497136.5136725122283136.13453155497235.871726723
 2283274.3441326497369.6229535452283363.51161715497368.349132337
#Sta/Elev= 30
       0 2426.68    16.7 2425.91    25.4 2424.55    32.2 2424.12    39.9 2422.71
    52.1 2423.65      67 2422.88    94.4 2418.75   111.4 2417.11   134.9  2416.4
   142.5 2416.59   173.8 2415.27   179.9 2414.61   284.7 2414.72   347.1  2415.5
   408.4 2415.16   451.2    2417   479.3 2417.09   485.2 2418.12   498.6 2414.37
   505.2 2413.09   515.4  2412.7   520.5 2412.86   527.9 2414.41   537.2 2416.46
   562.9  2417.8   676.4 2417.31   680.4 2417.87   696.4 2424.08   747.7 2449.09
#Mann= 11 ,-1,0
       0     .06       0   80.15     .05       0  138.66     .06       0
  280.57     .07       0  341.43     .06       0  451.43     .05       0
   498.6    .045       0   527.9     .06       0  574.29     .12       0
  644.39     .06       0  708.52     .08       0
#XS Ineff= 2 , 0
           481.7 2415.41   544.5         2418.25
Permanent Ineff=
       F       F
Bank Sta=498.6,527.9
XS Rating Curve= 0 ,0
Exp/Cntr(USF)=0,0
Exp/Cntr=0.5,0.3

Type RM Length L Ch R = 1 ,2297    ,624.5,646.4,664.5
BEGIN DESCRIPTION:
structure xs 2
END DESCRIPTION:
XS GIS Cut Line= 6
2282748.89288437497002.125535086 2282932.3231383497177.275951163
 2283046.3301364497228.2287994762283174.98607839  497346.0572612
2283246.32006603 497390.004092872283346.95194144497387.456450455
#Sta/Elev= 30
       0 2423.85    41.8 2420.97    83.8 2416.83   107.2 2416.33     115 2415.51
   117.2 2416.08   147.1 2415.23   157.5 2413.11   166.8 2415.35     177 2415.75
   314.3 2414.37   351.7 2415.57   413.9 2415.74   424.7 2413.81   433.5 2415.58
   451.3 2416.27   482.7 2414.93   489.8 2413.75   495.2 2412.93   511.5  2412.6
   525.2 2413.64   534.2 2415.91   547.8    2417   620.4 2416.72   655.3 2418.15
     671 2418.06   678.9 2417.14   694.3 2418.05     706 2421.78   737.7 2436.31
#Mann= 8 ,-1,0
       0     .06       0  247.66     .07       0  353.94     .06       0
   489.8    .045       0   525.2     .06       0  573.28     .05       0
  613.28     .06       0  707.06     .08       0
#XS Ineff= 2 , 0
           481.8    2415   533.2            2418
Permanent Ineff=
       F       F
Bank Sta=489.8,525.2
XS Rating Curve= 0 ,0
Exp/Cntr(USF)=0,0
Exp/Cntr=0.5,0.3

Type RM Length L Ch R = 1 ,1651    ,228.2,223.6,215.3
XS GIS Cut Line= 4
2282584.89850158496999.8779828062282735.85663567497334.215338986
2282900.18761248497484.7941068472283359.82184334497538.076446631
#Sta/Elev= 30
       0 2434.71    18.6 2434.21    27.8 2432.45    36.5 2425.36    40.9  2422.6
    67.3 2412.06    71.6 2410.93      76 2410.78    82.1    2412    84.8 2412.51
      98 2412.33   111.1 2413.64   128.7 2414.21   198.9 2413.91   277.9 2414.62
     327 2414.16   360.2 2414.79     372 2413.62   383.5 2413.95   400.8 2413.04
   428.6 2413.54   490.9 2413.23   567.3  2414.6   601.8 2414.69   613.9 2414.11
   629.8 2415.03     787 2415.86   875.6 2415.33  1008.3 2416.12  1052.4 2417.03
#Mann= 8 ,-1,0
       0     .06       0    67.3    .045       0    82.1     .06       0
     110      .1       0  406.84     .05       0  486.84     .06       0
  546.84     .05       0 1009.72     .06       0
#XS Ineff= 2 , 0
                          416.84          2418.4
Permanent Ineff=
       F       F
Bank Sta=67.3,82.1
XS Rating Curve= 0 ,0
Exp/Cntr(USF)=0,0
Exp/Cntr=0.3,0.1

Type RM Length L Ch R = 1 ,1427    ,287.3,298.1,318.5
XS GIS Cut Line= 4
2282370.41259648 497112.067821392282536.23643869497291.435871048
2282726.08500351497509.347038882 2283340.9275464497576.883591214
#Sta/Elev= 30
       0 2438.39    12.4 2438.28    24.7 2436.86      36 2432.45    50.2 2428.06
      70 2417.4289.792342410.273    98.3 2408.91114.49022410.219   121.4 2410.56
   135.1 2412.92   171.9  2411.7   197.3 2412.72   310.2  2413.8   323.3 2411.01
   335.5 2410.59   350.4 2410.78   367.4 2412.71   387.2 2412.66   401.4 2411.56
   416.4 2413.46   547.5  2414.4     640 2414.09   660.1 2414.72   716.5 2414.04
   744.6 2414.97   861.5 2415.03    1008 2416.38  1087.4 2415.79  1151.8 2416.66
#Mann= 5 ,-1,0
       0     .06       0      70      .1       089.79234    .045       0
114.4902      .1       0  533.29     .05       0
#XS Ineff= 2 , 0
                          424.42         2417.31
Permanent Ineff=
       F       F
Bank Sta=89.79234,114.4902
XS Rating Curve= 0 ,0
Exp/Cntr(USF)=0,0
Exp/Cntr=0.3,0.1

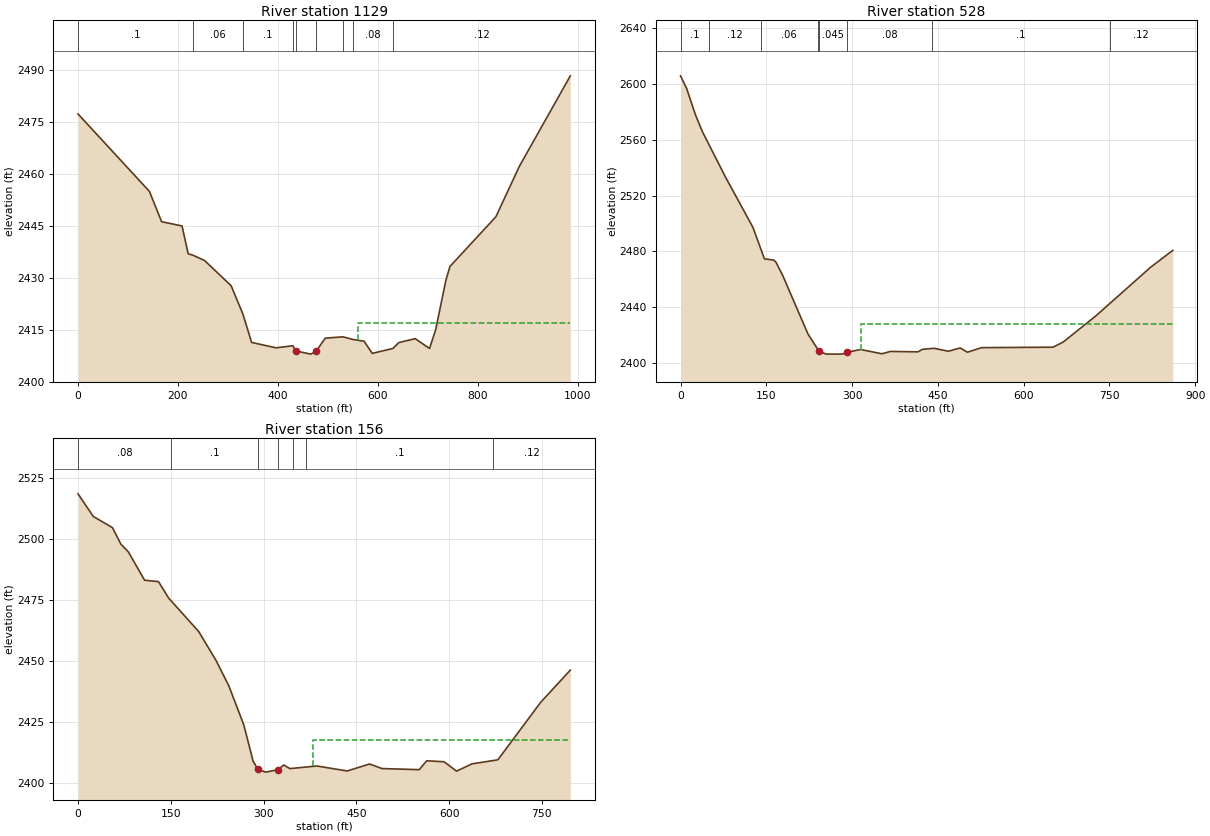
Type RM Length L Ch R = 1 ,1129    ,635.8,601.3,550.5
XS GIS Cut Line= 3
2282117.77510447496941.7518522522282279.58360958497690.258480385
2282453.14141162 497824.17155208
#Sta/Elev= 30
       0 2477.39   142.9 2454.99   167.2 2446.25   208.1 2445.01   220.4 2436.99
     2302436.551   253.1 2435.04   306.3 2427.75     3302419.516   347.3 2411.35
   396.4 2409.79     4302410.395   435.6  2408.9   465.7 2407.97     476 2408.73
   494.6 2412.58     5302412.974     5502412.211   572.3  2411.7   588.7 2408.19
     6302409.607   641.9 2411.32   674.7 2412.44   703.3  2409.6   715.6 2415.03
     736 2429.31   744.2 2433.32   836.1 2447.68   882.7 2462.17     985 2488.41
#Mann= 9 ,-1,0
       0      .1       0     230     .06       0     330      .1       0
     430     .08       0   435.6    .045       0     476     .08       0
     530      .1       0     550     .08       0     630     .12       0
#XS Ineff= 2 , 0
                          559.57         2416.83
Permanent Ineff=
       F       F
Bank Sta=435.6,476
XS Rating Curve= 0 ,0
Exp/Cntr=0.3,0.1

Type RM Length L Ch R = 1 ,528     ,371.3,371.3,371.3
XS GIS Cut Line= 3
2281601.64242283497707.1680838862282041.52031864  497733.4294508
2282445.66700004497848.663436985
#Sta/Elev= 30
       0    2606    10.6  2597.1    26.1 2578.09    38.6 2565.68    78.7 2533.37
   126.8 2497.18   146.8 2474.67   162.8 2473.86   166.8 2472.44   178.9 2462.67
   222.9 2420.82   242.5 2408.28     255 2406.36     283  2406.4   291.7 2407.78
   315.1 2409.66   352.2 2406.62   367.2 2408.29   415.3    2408   423.3 2409.82
   443.4 2410.54   468.4 2408.44   489.2 2410.79   501.7 2407.73   526.6 2411.01
   651.4 2411.34   669.2 2415.03   726.3 2433.77   821.9 2468.62   860.9  2480.8
#Mann= 8 ,-1,0
       0      .1       0      50     .12       0     140     .06       0
     240     .08       0   242.5    .045       0   291.7     .08       0
     440      .1       0  750.66     .12       0
#XS Ineff= 2 , 0
                          315.79         2428.16
Permanent Ineff=
       F       F
Bank Sta=242.5,291.7
XS Rating Curve= 0 ,0
Exp/Cntr=0.3,0.1

Type RM Length L Ch R = 1 ,156     ,,,
XS GIS Cut Line= 5
2281691.94242243498045.0075902422281955.87349092 498090.66053182
2282051.45933735498020.7544650292282245.48433906498039.300972545
2282459.48250271498057.847480061
#Sta/Elev= 30
       0 2518.59    24.6 2509.34    55.7 2504.72    69.2 2498.01    81.4  2494.8
   107.6 2483.19   130.1 2482.62   146.4 2475.92   195.1 2462.17   223.5 2450.16
   243.8 2439.92   267.9 2424.03   283.1 2409.06   290.7 2405.72   303.5 2404.56
   322.7 2405.54   332.6 2407.47   342.6 2406.01   386.3 2407.07   435.2 2405.03
   471.4 2407.89   491.5 2406.02   551.7 2405.57   563.8 2409.21   591.9 2408.81
     612 2404.96   637.1 2407.96   678.8  2409.6     748 2433.15     796 2446.36
#Mann= 7 ,-1,0
       0     .08       0     150      .1       0   290.7    .045       0
   322.7      .1       0  347.85     .08       0  367.85      .1       0
  671.18     .12       0
#XS Ineff= 2 , 0
                          380.63         2417.55
Permanent Ineff=
       F       F
Bank Sta=290.7,322.7
XS Rating Curve= 0 ,0
Exp/Cntr(USF)=0,0
Exp/Cntr=0.3,0.1
LCMann Table=0

Chan Stop Cuts=-1
Use User Specified Reach Order=0
Composite Channel Slope=5